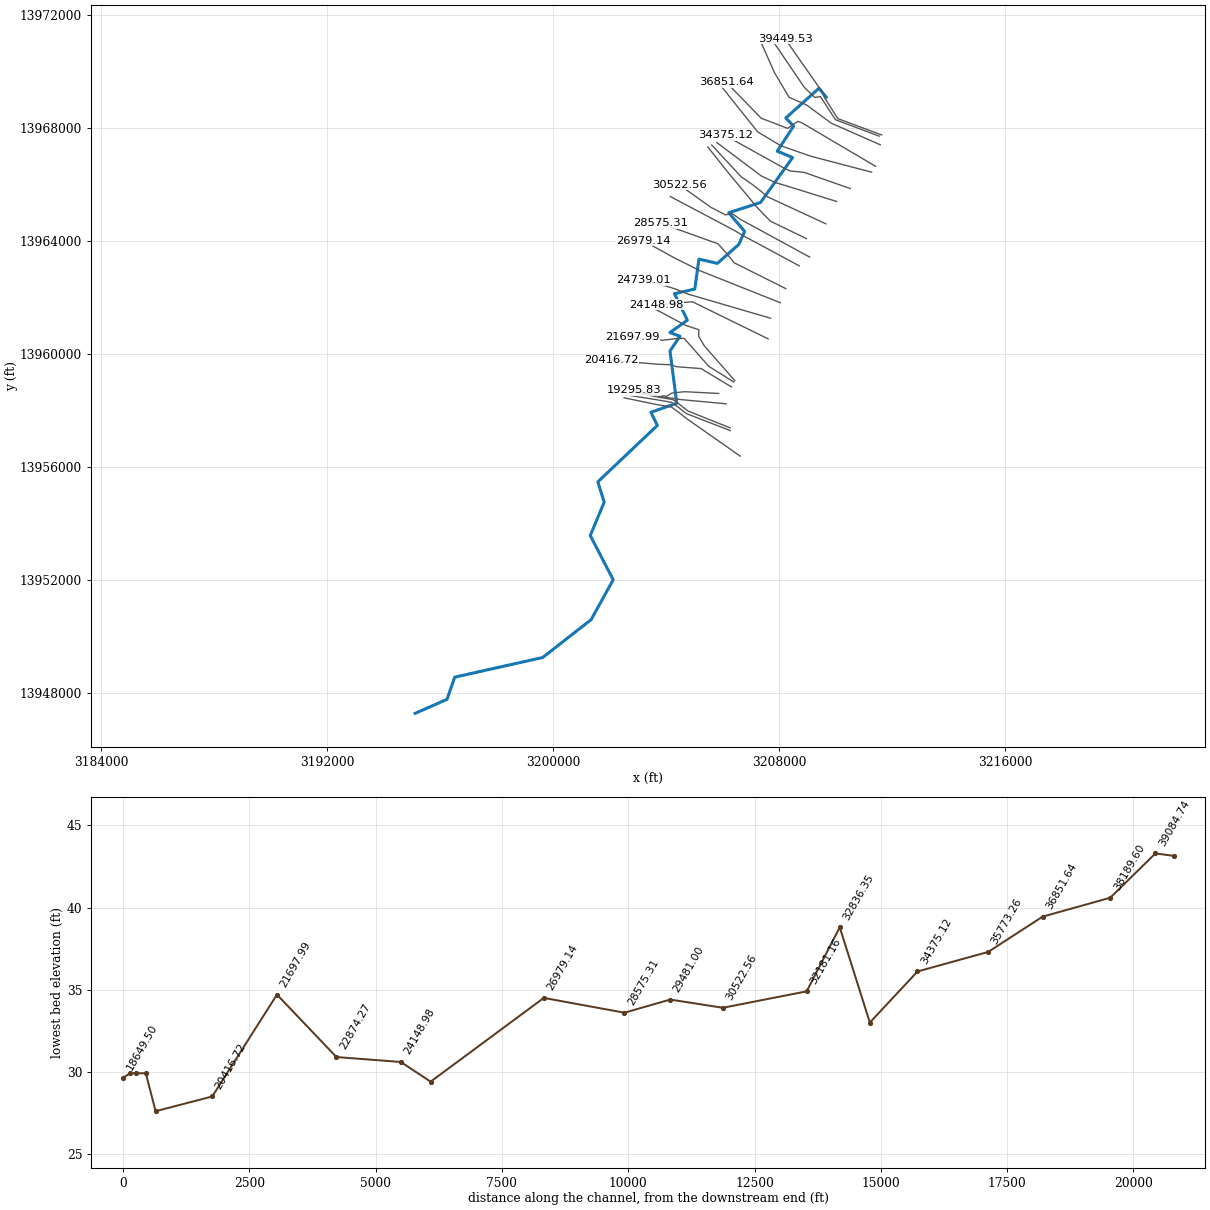
--- S100-00-00.prj (project) ---

Proj Title=S100-00-00
Current Plan=p03
Default Exp/Contr=.3,.1
English Units
Geom File=g02
Flow File=f01
Flow File=f02
Plan File=p01
Plan File=p03
Y Axis Title=Elevation
X Axis Title(PF)=Main Channel Distance
X Axis Title(XS)=Station
BEGIN DESCRIPTION:
Luce Bayou
Luce Bayou
HCFCD unit S100-00-00
(Flood Hazard, Floodway)Model
10, 2, 1, 0.2% Event
Filename S1000000.prj
Prepared by:  FTN Associates Ltd.   DATE:  May 2003
Reviewed by: 	 DATE:
STATUS (Final)
Calculated Normal Depth S = 0.00125, using the distance between the four most downstream cross sections and their inverts.  The flow data and manning's n came from HEC-2 data, dated July 1, 1980.
END DESCRIPTION:
DSS Export Rating Curves= 0
DSS Export Rating Curve Sorted= 0
DSS Export Volume Flow Curves= 0
DXF OffsetX= 0
DXF OffsetY= 0
DXF ScaleX= 1
DXF ScaleY= 10

--- S100-00-00.p03 (plan) ---

Plan Title=Floodway
Version=Version 3.0.1  Mar 2001
Short Identifier=Floodway0607
Geom File=g02
Flow File=f02
Subcritical Flow
K Sum by GR= 0
Std Step Tol= 0.01
Critical Tol= 0.01
Num of Std Step Trials= 20
Max Error Tol= 0.3
Flow Tol Ratio= 0.001
Split Flow NTrial= 30
Split Flow Tol= 0.02
Split Flow Ratio= 0.02
Log Output Level= 0
Friction Slope Method= 1
Unsteady Friction Slope Method= 2
Parabolic Critical Depth
Global Vel Dist= 0 , 0 , 0
Global Log Level= 0
CheckData=True
Encroach Param=-1 ,0,0, 2
Encroach River=S100-00-00
Encroach Reach=Luce Bayou
Encroach Node=39449.53
       1    2150    3180
Encroach Node=39084.74
       1    2170    3440
Encroach Node=38189.60
       1    2445    3760
Encroach Node=36851.64
       1    2708    4264
Encroach Node=35773.26
       1    2979    4350
Encroach Node=34375.12
       1    2181    3060
Encroach Node=33432.07
       1    1900    2670
Encroach Node=32836.35
       1    1620    2827
Encroach Node=32181.16
       1    1833    3050
Encroach Node=30522.56
       1    2165    3985
Encroach Node=29481.00
       1    2206    3650
Encroach Node=28575.31
       1    2170    3766
Encroach Node=26979.14
       1    2700    3976
Encroach Node=24739.01
       1    2730    3950
Encroach Node=24148.98
       1    2825    3740
Encroach Node=22874.27
       1    2050    3317
Encroach Node=21697.99
       1    2168    3441
Encroach Node=20416.72
       1    2057    2918
Encroach Node=19295.83
       1     960    2134
Encroach Node=19102.18
       1    1350    2380
Encroach Node=18905.98
       1    1700    2700
Encroach Node=18847.33
       1    1740    2780
Encroach Node=18788.67
       1    1763    2740
Encroach Node=18649.50
       1    2527    3550
Encroach Node=18029.28
       1    2550    3646
Encroach Node=17093.51
       1    2600    3600
Encroach Node=16165.96
       1    1988    3043
Encroach Node=15656.37
       1    1800    2582
Encroach Node=15136.36
       1    1615    2647
Encroach Node=15065.63
       1    1615    2635
Encroach Node=14994.91
       1    1615    2635
Encroach Node=14650.79
       1    1800    2783
Encroach Node=14410.33
       1    1865    2824
Encroach Node=13955.04
       1    2036    2895
Encroach Node=13461.20
       1    1808    2770
Encroach Node=12442.81
       1    1777    2342
Encroach Node=11482.19
       1    1345    2180
Encroach Node=10854.04
       1    1379    2115
Encroach Node=9973.591
       1     927    2200
Encroach Node=9769.326
       1     979    2300
Encroach Node=9678.981
       1     906    2500
Encroach Node=9588.635
       1     860    2350
Encroach Node=9337.589
       1     662    2000
Encroach Node=8295.254
       1    1285    1849
Encroach Node=7783.037
       1     948    1753
Encroach Node=6364.291
       1     907    2142
Encroach Node=5116.218
       1     578    1750
Encroach Node=3838.868
       1     573    1500
Encroach Node=2930.114
       1     500    1900
Encroach Reach=S100-00-00_0029
Encroach Node=39449.53
       1    2150    3180
Encroach Node=39084.74
       1    2170    3440
Encroach Node=38189.60
       1    2445    3760
Encroach Node=36851.64
       1    2708    4264
Encroach Node=35773.26
       1    2979    4350
Encroach Node=34375.12
       1    2181    3060
Encroach Node=33432.07
       1    1900    2670
Encroach Node=32836.35
       1    1620    2827
Encroach Node=32181.16
       1    1833    3050
Encroach Node=30522.56
       1    2165    3985
Encroach Node=29481.00
       1    2206    3650
Encroach Node=28575.31
       1    2170    3766
Encroach Node=26979.14
       1    2700    3976
Encroach Node=24739.01
       1    2730    3950
Encroach Node=24148.98
       1    2825    3740
Encroach Node=22874.27
       1    2050    3317
Encroach Node=21697.99
       1    2168    3441
Encroach Node=20416.72
       1    2057    2918
Encroach Node=19295.83
       1     960    2134
Encroach Node=19102.18
       1    1350    2380
Encroach Node=18905.98
       1    1700    2700
Encroach Node=18847.33
       1    1740    2780
Encroach Node=18788.67
       1    1763    2740
Encroach Node=18649.50
       1    2527    3550
Encroach Node=18029.28
       1    2550    3646
Encroach Node=17093.51
       1    2600    3600
Encroach Node=16165.96
       1    1988    3043
Encroach Node=15656.37
       1    1800    2582
Encroach Node=15136.36
       1    1615    2647
Encroach Node=15065.63
       1    1615    2635
Encroach Node=14994.91
       1    1615    2635
Encroach Node=14650.79
       1    1800    2783
Encroach Node=14410.33
       1    1865    2824
Encroach Node=13955.04
       1    2036    2895
Encroach Node=13461.20
       1    1808    2770
Encroach Node=12442.81
       1    1777    2342
Encroach Node=11482.19
       1    1345    2180
Encroach Node=10854.04
       1    1379    2115
Encroach Node=9973.591
       1     927    2200
Encroach Node=9769.326
       1     979    2300
Encroach Node=9678.981
       1     906    2500
Encroach Node=9588.635
       1     860    2350
Encroach Node=9337.589
       1     662    2000
Encroach Node=8295.254
       1    1285    1849
Encroach Node=7783.037
       1     948    1753
Encroach Node=6364.291
       1     907    2142
Encroach Node=5116.218
       1     578    1750
Encroach Node=3838.868
       1     573    1500
Encroach Node=2930.114
       1     500    1900
Computation Interval=1HOUR
Output Interval=1HOUR
Run HTab= 0
Run UNet= 0
Run PostProcess= 0
UNET Theta= 1
UNET ZTol= 0.02
UNET ZSATol= 0.1
UNET MxIter= 20
UNET MaxInSteps= 20
UNET DtIC= 0
UNET DtMin= 0
UNET MaxCRTS= 20
UNET WFStab= 2
UNET SFStab= 1
UNET WFX= 1
UNET SFX= 1
UNET Convert EG Bridges=-1
UNET Use Existing IB Tables=-1
Instantaneous Interval=1HOUR
Write IC File= 0
Write Velocity= 0
Write Detailed= 0

--- S100-00-00.p01 (plan) ---

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Plan Title=FEMA Effective June 2007
Short Identifier=FEMAeff0607
Geom File=g02
Flow File=f01
Encroach Param=-1 ,0,0, 0

--- S100-00-00.f02 (steady flow) ---

Flow Title=Floodway
Version=Version 3.0.1  Mar 2001
Number of Profiles= 2
Profile Names=1PCT_100yr,1PCTFloodway_100yrFW
River Rch & RM=S100-00-00,S100-00-00_0029 ,39449.53
   45700   45700
River Rch & RM=S100-00-00,S100-00-00_0029 ,39449.53
   45700   45700
Boundary for River Rch & Prof#=S100-00-00,S100-00-00_0029 , 1
Up Type= 0
Dn Type= 3
Dn Slope=.00125
Boundary for River Rch & Prof#=S100-00-00,S100-00-00_0029 , 2
Up Type= 0
Dn Type= 3
Dn Slope=.00125
DSS Import GetInterval= 0
DSS Import GetPeak= 0
DSS Import FillOption= 0

--- S100-00-00.f01 (steady flow) ---

Flow Title=FEMA Effective June 2007
Version=Version 3.0.1  Mar 2001
Number of Profiles= 4
Profile Names=10PCT_10yr,2PCT_50yr,1PCT_100yr,0.2PCT_500yr
River Rch & RM=S100-00-00,S100-00-00_0029 ,39449.53
   14650   33850   45700   84540
Boundary for River Rch & Prof#=S100-00-00,S100-00-00_0029 , 1
Up Type= 0
Dn Type= 3
Dn Slope=.00125
Boundary for River Rch & Prof#=S100-00-00,S100-00-00_0029 , 2
Up Type= 0
Dn Type= 3
Dn Slope=.00125
Boundary for River Rch & Prof#=S100-00-00,S100-00-00_0029 , 3
Up Type= 0
Dn Type= 3
Dn Slope=.00125
Boundary for River Rch & Prof#=S100-00-00,S100-00-00_0029 , 4
Up Type= 0
Dn Type= 3
Dn Slope=.00125
DSS Import GetInterval= 0
DSS Import GetPeak= 0
DSS Import FillOption= 0

--- S100-00-00.g02 (geometry) ---

Geom Title=S100-00-00 June 2007
Version=Version 3.0.1  Mar 2001

River Reach=S100-00-00      ,S100-00-00_0029
Reach XY= 30
     3209665.546    13969085.467     3209408.266    13969398.767
      3208233.91    13968346.826     3208509.863    13968058.424
     3207933.059     13967172.47     3208474.591    13966946.313
     3207339.657     13965356.99     3206217.172    13964993.894
     3206777.377    13964332.022     3206571.968    13963871.408
     3205812.579    13963203.312     3205161.081      13963352.7
     3205013.768     13962292.46     3204295.875    13962130.623
     3204752.339    13961190.723     3204131.963    13960755.008
     3204491.117    13960624.937     3204136.113     13960103.51
     3204376.794    13958252.758     3203461.792    13957933.233
     3203690.024     13957468.47     3201584.067     13955472.48
     3201808.493    13954753.567     3201316.413    13953571.932
     3202127.673    13952007.507     3201345.461    13950594.545
     3199631.648    13949256.277     3196519.397    13948561.207
     3196247.594     13947776.92     3195119.346    13947279.426

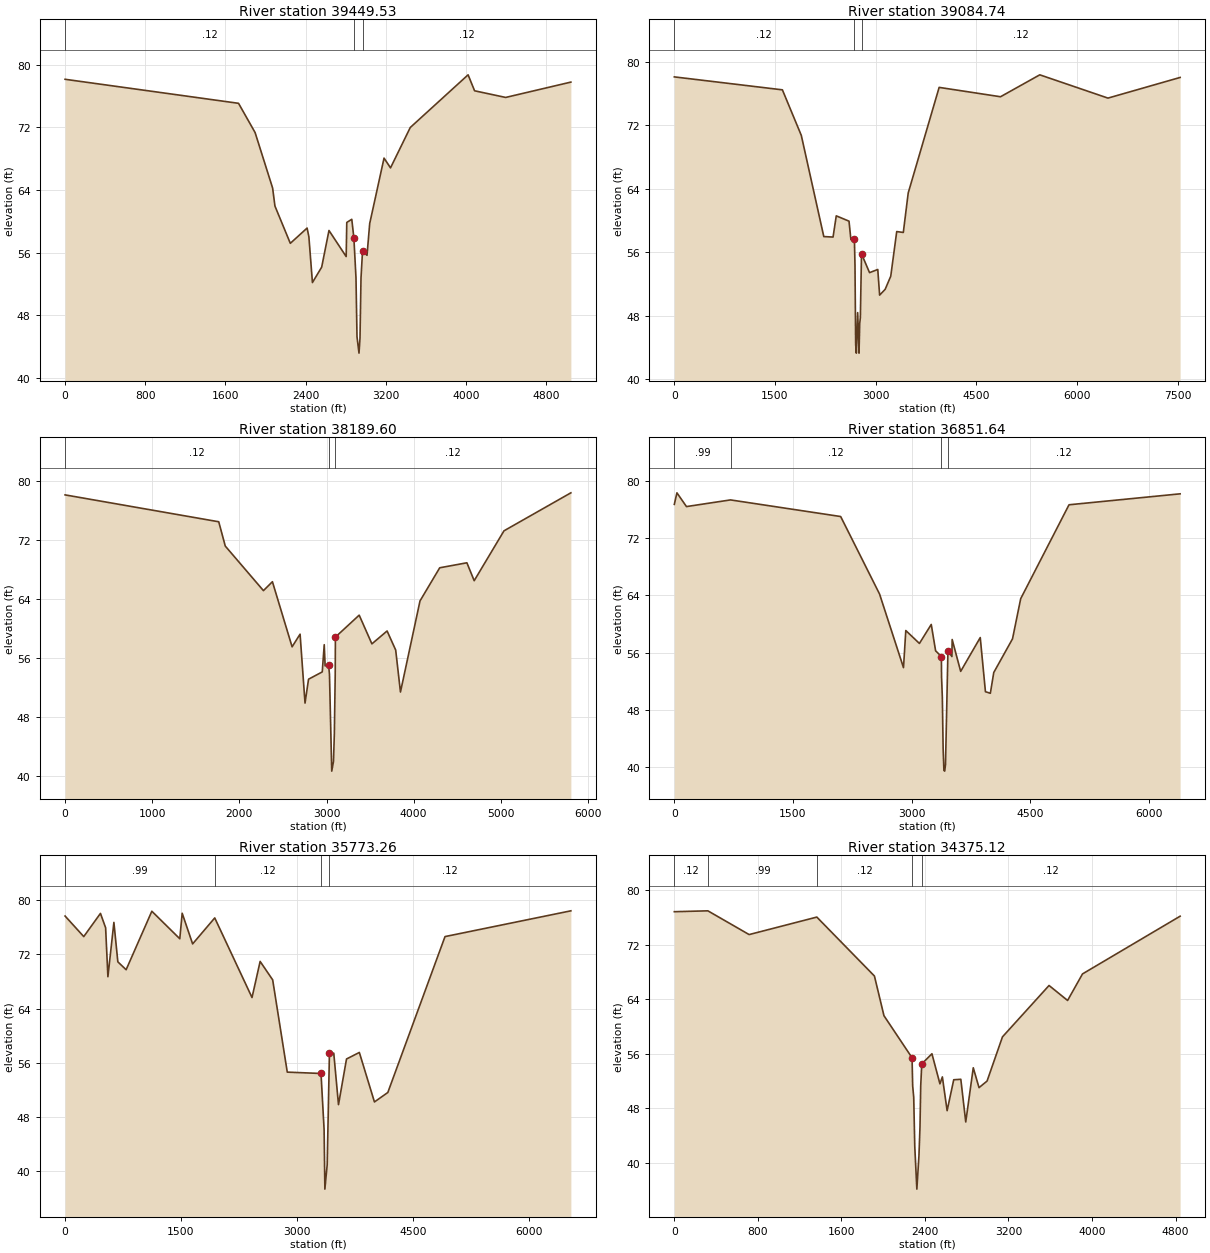
Type RM Length L Ch R = 1 ,39449.53,305,364.79,415
BEGIN DESCRIPTION:
481v1 used here, adj inv as needed based on survey data at nearest d/s sections.
Bank Station offset =      2067
END DESCRIPTION:
XS GIS Cut Line= 6
     3211627.738    13967745.959     3210071.732    13968325.704
      3209603.52    13969068.266     3209512.359    13969277.176
     3209356.626    13969508.877     3208208.657    13971148.483
#Sta/Elev= 30
       0   78.14 1730.78   75.07 1895.89   71.34 2070.95   64.24 2094.14   61.94
 2247.48   57.18    2415   59.13 2432.73   58.02  2468.2   52.17 2560.29   54.13
 2633.24   58.82 2804.86   55.49 2810.83   59.85 2860.83   60.25 2881.83   57.85
 2902.83   52.75 2912.83   45.25 2932.83   43.15 2942.83   45.05 2952.83   52.75
 2967.83   56.15 3012.83   55.65 3039.49    59.7 3182.68   68.07  3247.3   66.82
 3444.43   71.98 4021.43   78.71 4086.19   76.67 4396.35   75.82 5046.99   77.78
#Mann= 3 , 0 , 0
       0     .12       0 2881.83     .06       0 2967.83     .12       0
#Block Obstruct= 2 , 0
       0                    5030       0   78.21
Bank Sta=2881.83,2967.83
XS Rating Curve= 0
Exp/Cntr=.3,.1

Type RM Length L Ch R = 1 ,39084.74,504.22,895.14,576.27
BEGIN DESCRIPTION:
481v2
Bank Station offset =      2248
END DESCRIPTION:
XS GIS Cut Line= 6
     3211536.673    13967704.566     3209990.835     13968285.54
      3209459.09    13969106.783      3209260.72    13969072.098
     3208889.627    13969431.423     3207711.938     13971165.04
#Sta/Elev= 30
       0   78.07 1610.19   76.44 1891.68   70.71 2227.05   57.97 2364.87   57.91
 2412.79   60.58 2602.54   59.91 2630.77    57.6 2682.77    57.7 2691.77   54.31
 2701.77    44.4 2711.77    43.3 2731.77    48.4 2751.77    43.3 2761.77      47
 2771.77    47.8 2788.77    55.8 2908.72   53.43 3031.16   53.83 3058.85    50.6
 3141.04   51.33 3224.47   52.98 3313.44    58.6 3411.71   58.49 3484.71   63.46
 3945.55   76.75 4859.84   75.57 5445.02   78.33 6460.89    75.4 7535.87      78
#Mann= 3 , 0 , 0
       0     .12       0 2682.77     .06       0 2788.77     .12       0
Bank Sta=2682.77,2788.77
XS Rating Curve= 0
Exp/Cntr=.3,.1

Type RM Length L Ch R = 1 ,38189.60,630.07,1337.96,1131.19
BEGIN DESCRIPTION:
481v3
Bank Station offset =      1940
END DESCRIPTION:
XS GIS Cut Line= 6
     3211578.066    13967398.256     3209847.829    13968159.891
      3208967.29     13968808.71     3208350.632    13969079.807
     3207832.168    13969956.072     3207380.792    13970974.631
#Sta/Elev= 30
       0   78.11 1763.17   74.46 1838.27   71.16 2276.09   65.11 2379.19   66.32
 2604.99   57.48 2696.63    59.2 2753.33   49.84 2793.62   53.08 2950.96   54.07
 2973.75   57.77 2983.85    54.9 3023.85      55 3033.85   53.74 3059.85    40.6
 3079.85    41.9 3089.85    45.7 3099.85   53.74 3101.85    58.8 3374.89   61.78
 3520.75   57.88    3695   59.63 3793.68   57.04 3848.54   51.34 4072.66   63.71
 4298.89   68.21 4610.61   68.89 4694.65   66.46 5036.39   73.23 5803.93   78.39
#Mann= 3 ,-1 , 0
       0     .12       0 3023.85     .06       0 3101.85     .12       0
Bank Sta=3023.85,3101.85
XS Rating Curve= 0
Exp/Cntr=.3,.1

Type RM Length L Ch R = 1 ,36851.64,1029.72,1078.38,587.34
BEGIN DESCRIPTION:
481v4
Bank Station offset =      1580
END DESCRIPTION:
XS GIS Cut Line= 6
     3211412.493     13966636.62     3208789.657    13968183.413
     3208661.234    13968227.696     3208301.068    13967979.619
     3207363.728    13968338.405     3206130.717    13969608.654
#Sta/Elev= 30
       0    76.7   32.88   78.31   153.5   76.39  711.11   77.32 2104.11      75
 2595.89   64.18 2898.72    53.9  2927.8   59.08  3100.2   57.28 3249.82   59.93
 3304.99   56.25 3377.99   55.45 3379.99   52.66 3389.99   49.75 3399.99   42.65
 3409.99   39.55 3419.99   39.45 3429.99   40.35 3460.99   56.25 3510.99   55.45
 3514.27   57.83 3621.97   53.38 3869.57    58.1 3935.22   50.54 3997.33   50.32
 4040.46   53.22 4277.64   57.92 4381.21   63.53 4992.37   76.64 6397.71   78.17
#Mann= 4 ,-1 , 0
       0     .99       0  711.11     .12       0 3377.99     .06       0
 3460.99     .12       0
Bank Sta=3377.99,3460.99
XS Rating Curve= 0
Exp/Cntr=.3,.1

Type RM Length L Ch R = 1 ,35773.26,865.16,1398.14,825.06
BEGIN DESCRIPTION:
481v5 used here, adj inv as needed  based on data from nearest surveyed sections.
Bank Station offset =      1638
END DESCRIPTION:
XS GIS Cut Line= 6
     3211271.756    13966429.654      3209124.48    13966991.985
     3208171.535    13967324.815     3208023.398    13967385.589
     3207237.136    13967856.587     3205840.964    13969608.654
#Sta/Elev= 30
       0   77.68  241.65   74.64  457.84   78.07  524.66   75.95  554.27    68.7
   631.8   76.74  682.82   70.91  790.16   69.74 1122.88   78.39 1484.62   74.32
 1515.63   78.09 1650.75   73.56 1937.03    77.4  2419.4   65.63 2524.46   70.97
  2686.8   68.24 2875.71    54.6 3312.33    54.4 3352.33    46.1 3362.33    37.3
 3392.33    40.9 3421.33    57.4 3477.33    57.4 3538.58   49.79 3642.32   56.54
  3808.4   57.51 4003.88   50.19 4177.07   51.59 4917.12   74.64  6546.1   78.45
#Mann= 4 ,-1 , 0
       0     .99       0 1937.03     .12       0 3312.33     .06       0
 3421.33     .12       0
Bank Sta=3312.33,3421.33
XS Rating Curve= 0
Exp/Cntr=.3,.1

Type RM Length L Ch R = 1 ,34375.12,624.54,943.05,650.55
BEGIN DESCRIPTION:
481v6
Bank Station offset =      2677
END DESCRIPTION:
XS GIS Cut Line= 6
     3210512.518    13965850.938     3208881.901    13966422.449
     3208398.597    13966472.109      3208288.58    13966518.799
     3208209.825    13966552.257      3206089.44    13967728.128
#Sta/Elev= 30
       0   76.87  321.16      77  716.54   73.51 1364.58   76.08  1916.3   67.42
 2007.59   61.59 2276.53   55.41 2282.53   51.28 2292.53   49.61 2302.53    42.4
 2322.53   36.11 2342.53   41.01 2352.53   45.21 2359.53   51.28 2369.53   54.51
    2467      56 2543.54   51.58 2566.85    52.6 2612.37   47.64  2675.7   52.18
 2743.53   52.25 2790.76   45.98 2862.77   53.94 2917.96   51.02 2994.94   51.99
  3142.4   58.48 3588.49   66.03 3766.07   63.83 3908.87   67.73 4843.69   76.21
#Mann= 5 ,-1 , 0
       0     .12       0  321.16     .99       0 1364.58     .12       0
 2276.53     .06       0 2369.53     .12       0
Bank Sta=2276.53,2369.53
XS Rating Curve= 0
Exp/Cntr=.3,.1

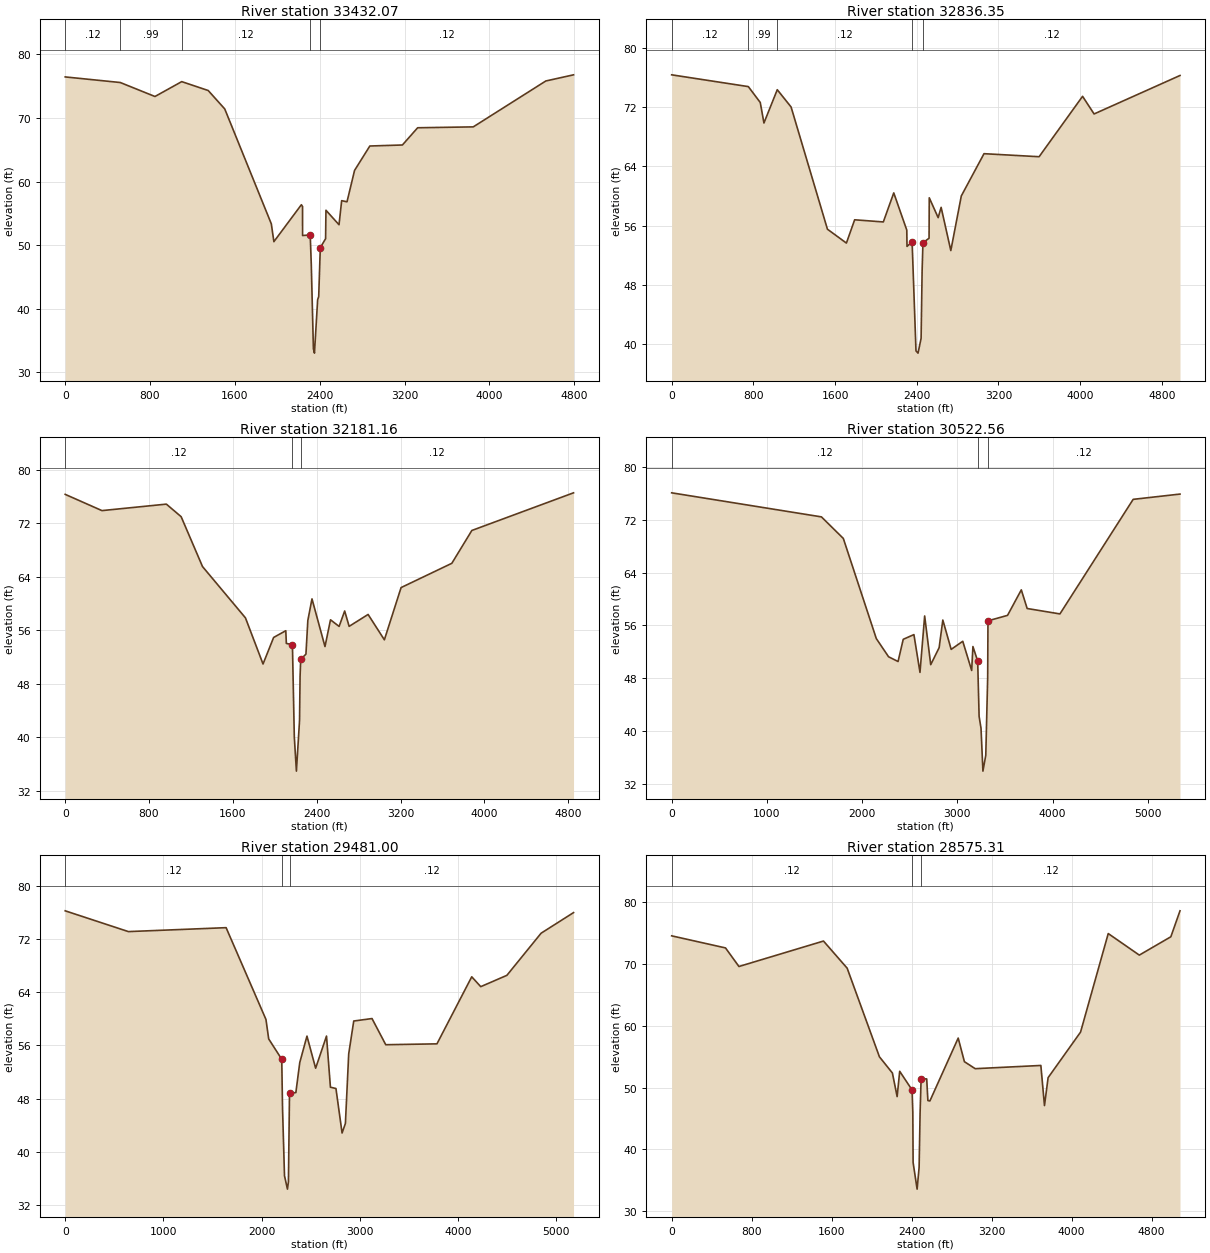
Type RM Length L Ch R = 1 ,33432.07,634.59,595.72,482.89
BEGIN DESCRIPTION:
481v7
Bank Station offset =      2650
END DESCRIPTION:
XS GIS Cut Line= 6
     3210037.178    13965391.711     3208281.566    13965937.334
     3207899.615    13966050.394     3207701.218    13966138.767
     3207372.463    13966294.156     3205791.346    13967478.373
#Sta/Elev= 30
       0   76.46  519.15   75.58  846.32   73.38 1098.75   75.72 1348.53   74.32
 1504.41   71.42 1943.51   53.34 1967.74   50.54 2226.78   56.35 2238.13   56.06
 2238.24    51.5 2310.24    51.6 2320.24   46.98 2340.24    33.7 2350.24      33
 2380.24    41.4 2390.24    41.9 2405.24    49.6 2455.24      51 2458.61   55.48
 2581.88    53.2 2606.71   56.99 2657.11   56.81 2728.37   61.75 2872.27   65.59
 3179.53   65.75 3323.27   68.46 3847.75    68.6 4531.63   75.82 4793.02   76.79
#Mann= 5 ,-1 , 0
       0     .12       0  519.15     .99       0 1098.75     .12       0
 2310.24     .06       0 2405.24     .12       0
Bank Sta=2310.24,2405.24
XS Rating Curve= 0
Exp/Cntr=.3,.1

Type RM Length L Ch R = 1 ,32836.35,623.41,655.19,515.84
BEGIN DESCRIPTION:
481v8 used here, adj inv based on inverts at nearest surveyed sections.
Bank Station offset =      2588
END DESCRIPTION:
XS GIS Cut Line= 6
     3209650.461    13964602.164     3207576.869    13965562.752
     3207394.831    13965722.945     3207059.015    13965986.843
     3206651.518    13966270.686       3205614.1     13967389.75
#Sta/Elev= 30
       0   76.35  750.66   74.76  867.39   72.62  903.59   69.85 1033.99   74.34
 1169.31   72.01 1525.27   55.52 1710.96   53.65 1791.68   56.79 2072.49    56.5
  2174.6   60.42  2302.2    55.4 2304.33    53.2 2354.33    53.8 2392.33    39.1
 2412.33    38.8 2442.33    40.8 2452.33    49.9 2460.33    53.7 2520.33    54.3
  2522.2   59.76  2609.5   57.08 2638.46   58.47 2733.39   52.64 2836.11   60.01
 3058.35   65.71 3597.78    65.3 4023.47   73.45  4136.3   71.07 4977.43   76.26
#Mann= 5 ,-1 , 0
       0     .12       0  750.66     .99       0 1033.99     .12       0
 2354.33     .06       0 2460.33     .12       0
Bank Sta=2354.33,2460.33
XS Rating Curve= 0
Exp/Cntr=.3,.1

Type RM Length L Ch R = 1 ,32181.16,983.62,1658.6,1085.55
BEGIN DESCRIPTION:
481v9 used here, adj inv as needed based on data from nearest surveyed sections.
Bank Station offset =      2794
END DESCRIPTION:
XS GIS Cut Line= 6
      3208965.65    13964078.484     3207689.225     13964695.49
     3207176.387    13965227.804     3207110.307    13965314.923
     3206151.154    13966468.984     3205477.138    13967317.241
#Sta/Elev= 30
       0   76.29  350.68   73.86   965.1   74.83  1106.3   72.95 1310.28   65.49
 1719.88   57.82 1887.68   50.92 1988.62   54.89 2104.75    55.9 2110.08      54
 2168.08    53.8 2186.08      40 2206.08    34.9 2236.08    42.5 2241.08   49.08
 2247.08    51.6 2297.08    52.4 2315.05   57.42 2354.76   60.66 2478.77   53.53
 2531.39   57.53  2613.6   56.54 2666.56   58.85 2709.16   56.55 2890.24   58.33
 3045.42   54.54 3204.85   62.35 3689.11   65.98 3880.09   70.89 4850.29   76.52
#Mann= 3 , 0 , 0
       0     .12       0 2168.08     .06       0 2247.08     .12       0
Bank Sta=2168.08,2247.08
XS Rating Curve= 0
Exp/Cntr=.3,.1

Type RM Length L Ch R = 1 ,30522.56,703.76,1041.56,343.9
BEGIN DESCRIPTION:
481v10
Bank Station offset =      1732
END DESCRIPTION:
XS GIS Cut Line= 6
     3209078.442    13963425.899     3206612.071     13964769.07
     3206337.003    13964966.295     3206099.733    13964918.841
     3205589.931    13965182.239     3204470.062    13965979.844
#Sta/Elev= 30
       0   76.12 1572.57   72.47 1802.38    69.2 2148.68   54.01 2277.34   51.25
 2377.06   50.53 2431.55    53.9 2543.64   54.61  2607.4   48.88 2656.39   57.44
 2720.18   50.05  2808.4   52.63 2847.16   56.82 2934.78   52.37 3056.55    53.6
 3150.09   49.17 3163.19    52.8 3213.19    50.6 3228.19    42.2 3248.19    40.4
 3268.19    33.9 3298.19    36.3 3318.19   48.16 3321.19    56.7 3526.77   57.53
 3671.21    61.4 3732.81   58.57 4076.79   57.75 4845.83   75.13 5337.53   75.93
#Mann= 3 , 0 , 0
       0     .12       0 3213.19     .06       0 3321.19     .12       0
Bank Sta=3213.19,3321.19
XS Rating Curve= 0
Exp/Cntr=.3,.1

Type RM Length L Ch R = 1 ,29481.00,1003.46,905.69,738.26
BEGIN DESCRIPTION:
481v11
Bank Station offset =      2736
END DESCRIPTION:
XS GIS Cut Line= 6
     3208712.216    13963113.313     3207130.999    13963966.547
     3206818.295    13964129.463     3206656.514    13964222.907
     3206437.051    13964356.582     3204151.231    13965565.956
#Sta/Elev= 30
       0    76.2  643.77   73.08 1639.35   73.67 2045.29   59.89 2073.35   56.96
 2206.32    53.9 2214.32   46.53 2234.32    36.4 2264.32    34.4 2274.32    35.5
 2285.32    48.8  2350.1    48.9 2389.96   53.42 2463.17   57.38 2551.56   52.56
 2662.29   57.39 2702.28   49.71 2758.52   49.51 2821.07   42.83 2854.92   44.27
 2888.51   54.71 2939.86   59.65 3125.95   60.02 3265.95   56.09 3787.64   56.22
 4141.99   66.29 4233.96   64.81  4500.1   66.51 4848.93   72.84 5179.16   75.93
#Mann= 3 , 0 , 0
       0     .12       0 2206.32     .06       0 2285.32     .12       0
Bank Sta=2206.32,2285.32
XS Rating Curve= 0
Exp/Cntr=.3,.1

Type RM Length L Ch R = 1 ,28575.31,1074.64,1596.17,1184.21
BEGIN DESCRIPTION:
481v12
Bank Station offset =      2545
LOB not blocked, assuming divided flow goes into Mexican Gully.
END DESCRIPTION:
XS GIS Cut Line= 6
     3208235.135    13962308.443     3206405.173    13963224.376
     3206212.675    13963464.426     3206103.227    13963595.101
     3205841.197    13963891.745     3203805.301    13964624.256
#Sta/Elev= 30
       0    74.5  538.39   72.55  672.88   69.55 1518.41   73.66 1755.11   69.28
 2077.77   54.97 2207.61   52.35    2255   48.54 2280.54   52.63 2404.74    49.6
 2411.74   46.01 2414.74    37.9 2454.74    33.6 2474.74    37.1 2484.74   46.01
 2494.74    51.4 2550.74    51.4 2562.59    47.9 2582.63   47.84 2865.67   57.99
 2927.74   54.18 3035.87   53.05 3692.38   53.57 3728.71   47.09 3764.91    51.6
 4089.29   58.95 4366.37   74.87 4677.14   71.39 4992.47   74.35 5084.01   78.54
#Mann= 3 ,-1 , 0
       0     .12       0 2404.74     .06       0 2494.74     .12       0
Bank Sta=2404.74,2494.74
XS Rating Curve= 0
Exp/Cntr=.3,.1

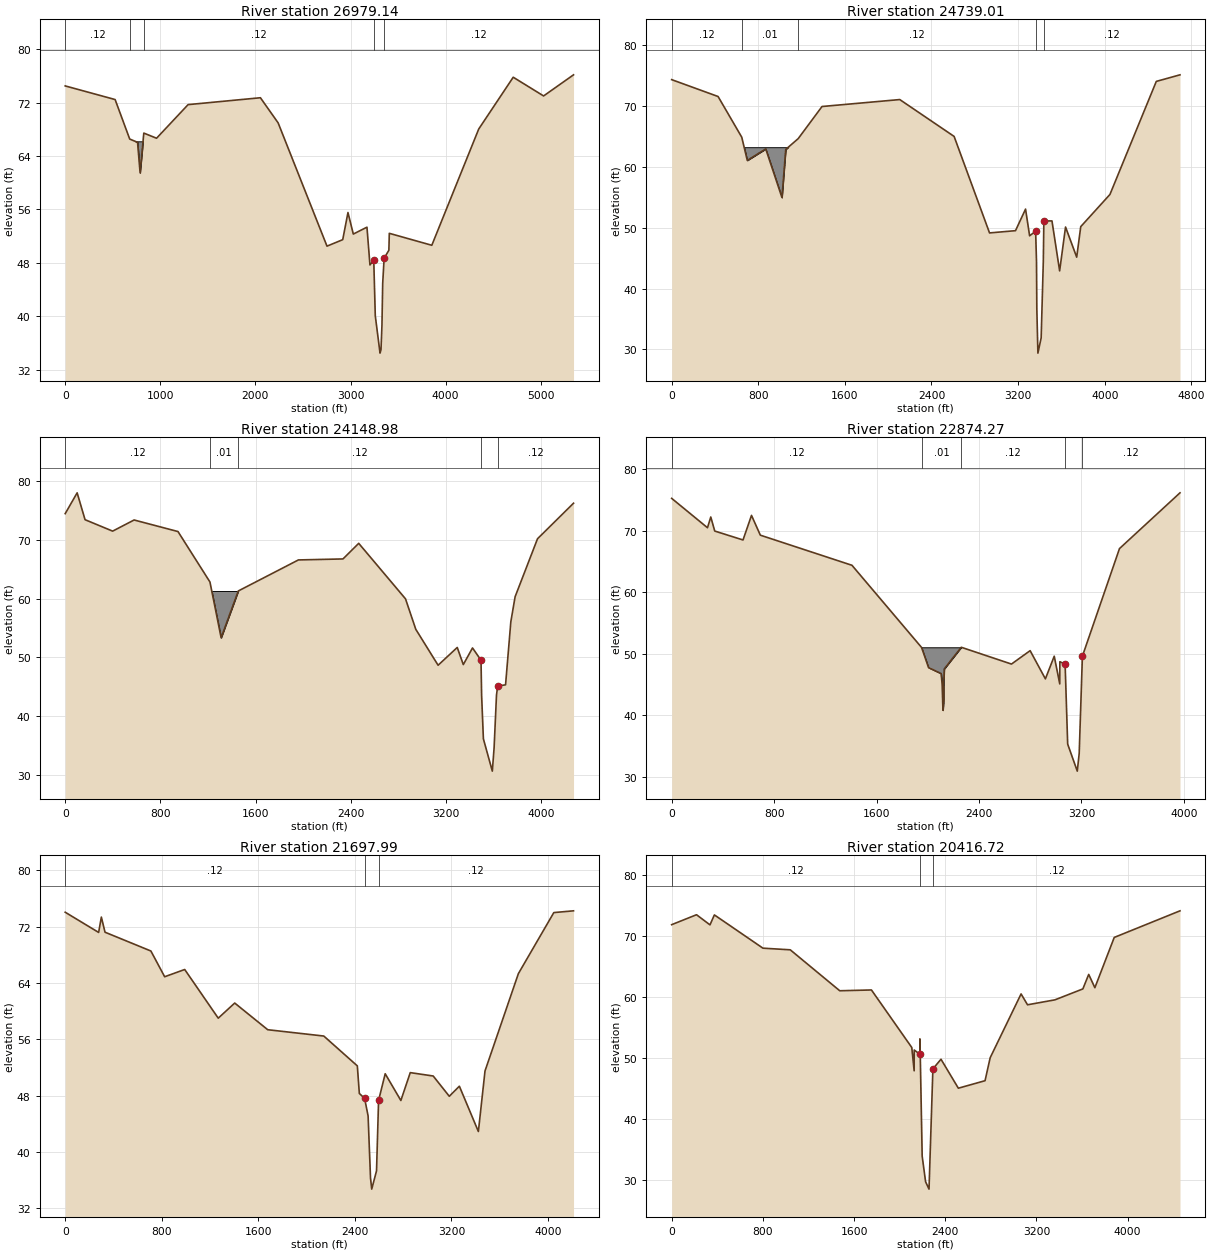
Type RM Length L Ch R = 1 ,26979.14,953.91,2240.14,1041.82
BEGIN DESCRIPTION:
481v13 used here
Bank Station offset =      1689
LOB blocked and Manning's = .01 at channel of Mexican Gully, assuming divided flow goes into Mexican Gully.
END DESCRIPTION:
XS GIS Cut Line= 5
     3208042.951    13961808.765     3205163.054    13962955.979
     3204857.232    13963116.171      3204311.12    13963385.587
     3203180.704    13964009.268
#Sta/Elev= 30
       0   74.49  524.88   72.45   678.2   66.54  760.71   66.05  787.64   61.48
   826.5   67.43  960.58   66.66 1292.29   71.69 2052.69   72.72 2239.05   68.96
 2752.82   50.51 2918.27   51.48  2973.3   55.54 3029.48   52.32 3173.01   53.35
 3204.55    47.7 3244.55    48.4 3260.55    40.1 3310.55    34.5 3320.55      35
 3330.55    38.6 3338.55   44.93 3353.55    48.7 3403.55    49.9 3408.06   52.43
 3855.02   50.64  4348.4   68.04 4711.11   75.79 5030.54   72.99 5345.23   76.15
#Mann= 5 ,-1 , 0
       0     .12       0   678.2     .01       0   826.5     .12       0
 3244.55     .06       0 3353.55     .12       0
#Block Obstruct= 2 , 0
       0     830    66.2               0
Bank Sta=3244.55,3353.55
XS Rating Curve= 0
Exp/Cntr=.3,.1

Type RM Length L Ch R = 1 ,24739.01,286.61,590.03,596.97
BEGIN DESCRIPTION:
481v14 used here
Bank Station offset =      1617
LOB blocked and Manning's = .01 at channel of Mexican Gully, assuming divided flow goes into Mexican Gully.
END DESCRIPTION:
XS GIS Cut Line= 6
      3207697.02    13961261.042     3204789.496    13962110.728
     3204520.863    13962214.892      3204372.84     13962280.68
     3204137.101    13962357.433     3203202.101    13962609.437
#Sta/Elev= 30
       0   74.29  428.74   71.52  647.44   64.84  698.52   61.03  869.06   62.92
  1018.8   54.94 1053.76   62.84 1168.52    64.6 1388.87   69.88    2107   71.02
    2609   64.97 2936.25   49.13 3176.03    49.5 3268.87   53.04 3306.41   48.66
    3362    49.4    3370   44.46    3373    36.7    3383    29.4    3413    31.9
    3433   44.46    3438    51.1    3513    51.1 3583.69    42.9 3638.32    50.1
 3741.39   45.15  3778.7   50.16  4048.3   55.44 4476.66      74 4695.53   75.08
#Mann= 5 ,-1 , 0
       0     .12       0  647.44     .01       0 1168.52     .12       0
    3362     .06       0    3438     .12       0
#Block Obstruct= 2 , 0
       0    1140    63.2               0
Bank Sta=3362,3438
XS Rating Curve= 0
Exp/Cntr=.3,.1

Type RM Length L Ch R = 1 ,24148.98,991.21,1274.71,497.72
BEGIN DESCRIPTION:
481v15
Bank Station offset =      1411
LOB blocked and Manning's = .01 at channel of Mexican Gully, assuming divided flow goes into Mexican Gully.
END DESCRIPTION:
XS GIS Cut Line= 6
     3207610.538    13960530.744     3204932.224    13961842.772
     3204466.611    13961805.886     3204232.363    13961785.418
     3203806.771    13961743.123     3203647.684    13961743.836
#Sta/Elev= 30
       0   74.49  100.28   78.04  166.79   73.46  398.73   71.51  579.01   73.41
  947.67   71.44 1216.28   62.84 1310.32   53.33 1454.41   61.31 1959.51    66.6
 2334.07   66.77 2466.46   69.43 2859.51   59.97 2945.81   54.78 3133.38   48.65
 3294.26   51.68  3345.2   48.76 3422.63    51.6 3494.01    49.5 3499.01   43.55
 3514.01    36.1 3589.01    30.6 3604.01    34.6 3624.01   43.55 3634.01    45.1
 3700.23   45.31  3744.5   56.05  3780.4   60.32  3968.8   70.21  4271.4   76.27
#Mann= 5 ,-1 , 0
       0     .12       0 1216.28     .01       0 1454.41     .12       0
 3494.01     .06       0 3634.01     .12       0
#Block Obstruct= 2 , 0
       0    1460    61.3               0
Bank Sta=3494.01,3634.01
XS Rating Curve= 0
Exp/Cntr=.3,.1

Type RM Length L Ch R = 1 ,22874.27,613.67,1176.28,862.11
BEGIN DESCRIPTION:
481v16 (and 482 s1d added)
Blocked and Manning's = 0.1 at Mexican Gully.
The Mexican and Luce drainage areas are dissimilar and coincident peaks are not modeled.
Bank Station offset =      1833
END DESCRIPTION:
XS GIS Cut Line= 6
     3206430.001    13959053.575     3205349.686    13960285.179
     3205150.205    13960627.143     3205157.304    13960854.319
     3204685.616    13961012.085     3203623.461    13961578.129
#Sta/Elev= 30
       0   75.28  279.73    70.5  305.36   72.25  336.44   69.96  557.17   68.51
  623.43   72.51  692.45   69.29 1407.94   64.39 1951.48   51.02 2005.96   47.74
    2104   46.77 2112.05   45.05 2118.46    40.8 2123.41   42.12 2124.43   45.05
 2128.61   47.53 2261.45   51.05 2653.58   48.32 2799.12    50.5 2918.41   45.91
  2987.4    49.6 3030.52   45.09 3031.37    48.7 3072.37    48.3 3092.37    35.3
 3167.37    30.9 3182.37    33.8 3207.37    49.6 3497.01   67.11 3969.47   76.18
#Mann= 5 ,-1 , 0
       0     .12       0 1951.48     .01       0 2261.45     .12       0
 3072.37     .06       0 3207.37     .12       0
#Block Obstruct= 2 , 0
       0    2261   51.05               0
Bank Sta=3072.37,3207.37
XS Rating Curve= 0
Exp/Cntr=.3,.1

Type RM Length L Ch R = 1 ,21697.99,1017.68,1281.27,891.54
BEGIN DESCRIPTION:
481v17 (and 482v3 on left side)  Extended LOB to show complete cross section.
Bank Station offset =      2460
END DESCRIPTION:
XS GIS Cut Line= 6
     3206399.781    13959002.884     3205513.451    13959555.826
     3204638.946    13960546.722     3204369.638    13960541.761
     3203872.646    13960481.546     3202805.946    13960598.008
#Sta/Elev= 30
       0   74.06  277.01   71.19  299.57   73.37  329.92   71.22  709.97   68.55
  824.03   64.89  990.25   65.92 1268.11      59 1404.57   61.15 1678.06   57.36
 2142.68   56.46 2420.54   52.22  2437.2    48.3 2480.85    47.6 2509.79    45.1
 2529.74    36.3 2539.72    34.7 2579.64    37.3  2596.6    47.3 2651.48    51.1
 2781.25    47.3 2859.16   51.26  3049.2   50.78 3182.44    47.9 3266.04   49.33
 3423.58   42.89 3478.54    51.5 3754.95   65.33 4048.66   74.01 4211.98   74.26
#Mann= 3 , 0 , 0
       0     .12       0 2480.85     .06       0  2596.6     .12       0
Bank Sta=2480.85,2596.6
XS Rating Curve= 0
Exp/Cntr=.3,.1

Type RM Length L Ch R = 1 ,20416.72,901.84,1120.89,1131.68
BEGIN DESCRIPTION:
481v18
Bank Station offset =      2743
END DESCRIPTION:
XS GIS Cut Line= 6
     3206313.298    13958829.918     3205236.764    13959479.676
     3204369.592    13959545.004     3204174.644    13959616.082
     3203743.379    13959630.635     3202056.429    13959771.618
#Sta/Elev= 30
       0   71.84  217.92   73.47  335.96   71.81  374.71   73.44  800.56   67.99
 1040.24   67.72 1474.36   61.01 1752.38   61.14 2106.19   51.71 2127.09   47.89
 2127.42    51.3 2177.42    50.6 2177.42   53.12 2180.42    50.6 2197.42    33.9
 2227.42    29.7 2257.42    28.5 2291.42    48.2 2362.45   49.79 2514.66   45.04
 2748.91   46.27 2793.82   50.03 3064.95   60.49 3121.45   58.71 3361.89   59.52
 3606.84   61.31 3658.21   63.69  3712.2   61.51 3882.18   69.75 4458.94   74.11
#Mann= 3 , 0 , 0
       0     .12       0 2180.42     .06       0 2291.42     .12       0
Bank Sta=2180.42,2291.42
XS Rating Curve= 0
Exp/Cntr=.3,.1

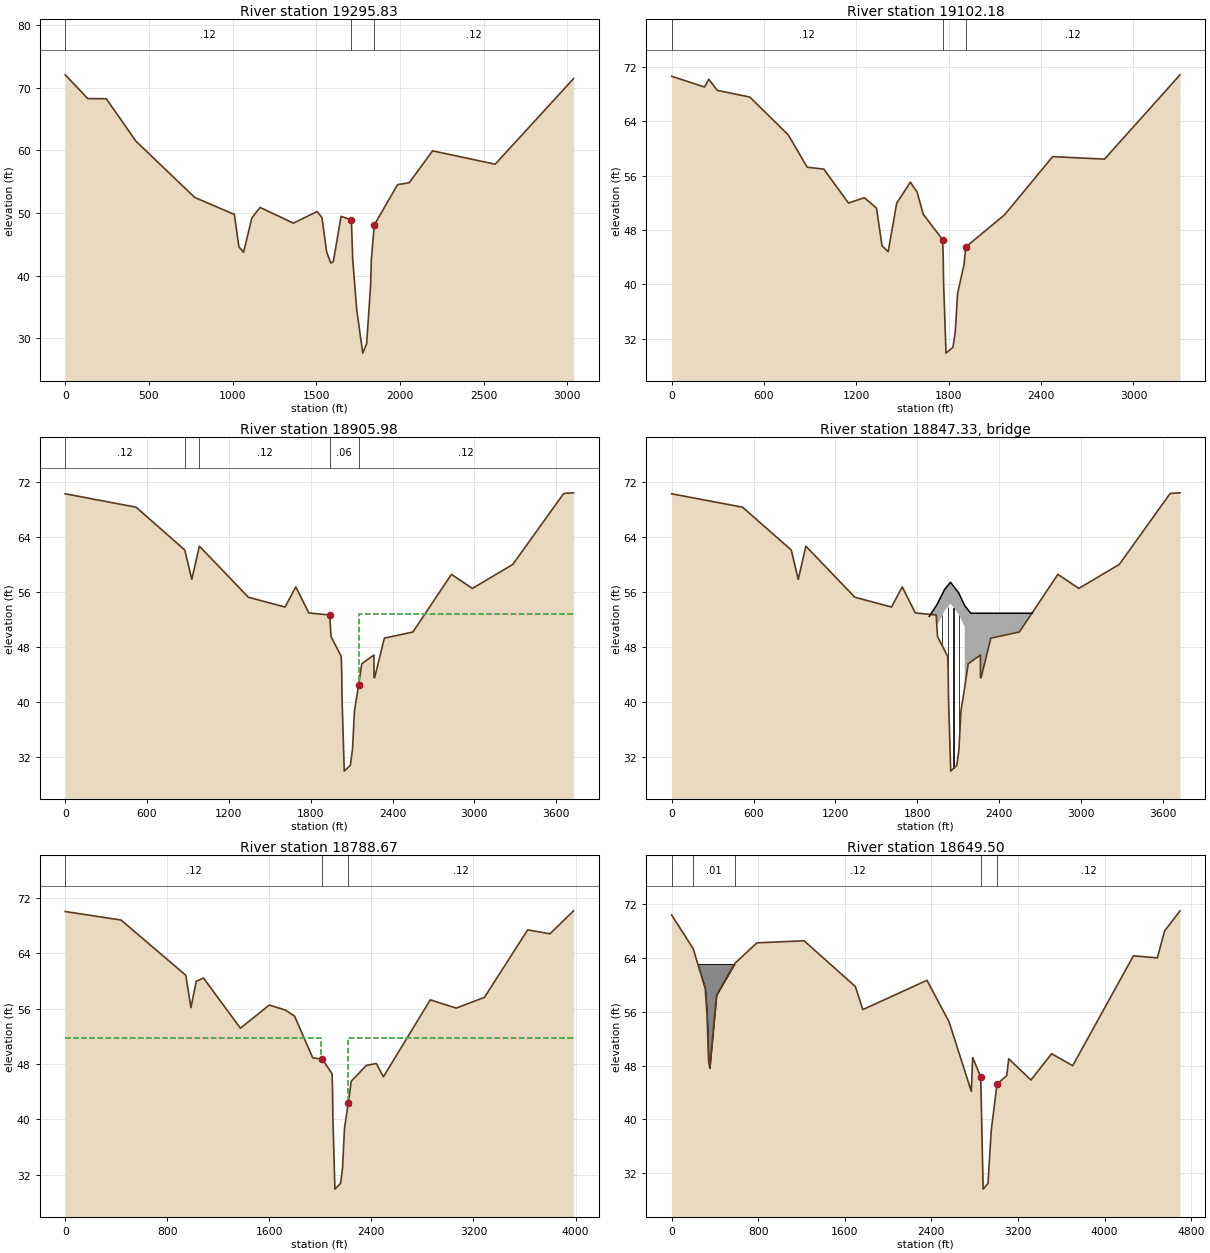
Type RM Length L Ch R = 1 ,19295.83,312.31,193.65,31.28
BEGIN DESCRIPTION:
481v19
Bank Station offset =      3210
END DESCRIPTION:
XS GIS Cut Line= 6
     3205861.666    13958599.298      3204656.92    13958661.982
     3204207.695    13958613.051      3204014.68    13958500.866
     3203666.026    13958536.574     3202881.705    13958716.558
#Sta/Elev= 30
       0   72.07  135.38   68.27  245.55   68.25   422.7   61.46  774.08   52.47
 1010.62   49.76  1037.5   44.61  1065.4   43.71 1115.27   49.21 1164.22   50.88
 1363.29   48.37 1505.18   50.23 1533.85   49.25 1562.09   43.72 1586.82      42
 1601.54   42.21 1647.94   49.45 1709.66    48.9 1717.66   42.56 1741.66    34.5
 1777.66    27.6 1800.66    29.1 1824.66    38.5 1828.66   42.56 1846.66    48.1
 1985.59   54.53 2054.71   54.81 2194.57   59.92 2568.81   57.79 3036.69   71.46
#Mann= 3 , 0 , 0
       0     .12       0 1709.66     .06       0 1846.66     .12       0
Bank Sta=1709.66,1846.66
XS Rating Curve= 0
Exp/Cntr=.3,.1

Type RM Length L Ch R = 1 ,19102.18,256.06,196.2,37.71
BEGIN DESCRIPTION:
481s3  XS 4/4, copy of 481s3d
Bank Station offset =      3218
END DESCRIPTION:
XS GIS Cut Line= 6
     3206121.114    13958234.149     3204491.124     13958385.28
      3204284.63    13958421.507     3203922.259    13958472.842
     3203244.434    13958592.268     3202853.992     13958685.78
#Sta/Elev= 30
       0    70.6  213.48   69.02  240.76   70.16  296.66   68.53  507.67   67.54
  756.29   62.02  880.85   57.23  988.23   56.96 1148.56   51.97  1251.5   52.75
 1330.75   51.22 1366.85   45.66 1406.55   44.82  1461.7   51.93 1550.51   55.04
 1594.86   53.56 1634.38   50.32 1760.16   46.59 1763.91   44.26 1766.25   40.41
 1782.32   29.91 1827.32   30.76 1842.32   33.01 1857.32   38.66 1898.93    42.9
  1910.7   45.51 2162.82   50.24 2475.31   58.79 2812.08   58.42 3302.37   70.81
#Mann= 3 , 0 , 0
       0     .12       0 1760.16     .06       0  1910.7     .12       0
Bank Sta=1760.16,1910.7
XS Rating Curve= 0
Exp/Cntr=.5,.3

Type RM Length L Ch R = 1 ,18905.98,109.7,117.31,113
BEGIN DESCRIPTION:
481s3  XS 3/4, copy of 481s3d
Bank Station offset =      2954
LOB Manning's of .99 b/c area does not convey flow but similar area downsrtream does convey flow
END DESCRIPTION:
XS GIS Cut Line= 6
     3206263.968    13957382.583     3204767.192    13957981.606
     3204466.861    13958219.086     3204243.496    13958380.907
     3203702.881     13958473.64      3202813.93    13958648.783
#Sta/Elev= 30
       0   70.22  519.77   68.27  876.75   62.05  928.09   57.78  983.83   62.61
 1342.41   55.19 1611.69   53.76 1690.49   56.69 1786.04   52.91 1939.13    52.6
 1949.04   49.47 2023.63   46.59 2027.38   44.26 2029.72   40.41 2045.79   29.91
 2090.79   30.76 2105.79   33.01 2120.79   38.66 2150.79   42.41 2174.17   45.51
 2263.86   46.79 2263.91    43.5 2268.65    43.5 2340.04   49.24 2549.12   50.13
 2831.53   58.51 2985.36   56.47 3281.44   59.95 3654.76   70.27 3726.76   70.36
#Mann= 5 ,-1 , 0
       0     .12       0  876.75     .99       0  983.83     .12       0
 1939.13     .06       0 2150.79     .12       0
#XS Ineff= 2 , 0
       0    1935    52.4    2155       0    52.8
Permanent Ineff=
       F       F
Bank Sta=1939.13,2150.79
XS Rating Curve= 0
Exp/Cntr=.5,.3

Type RM Length L Ch R = 3 ,18847.33,,,
BEGIN DESCRIPTION:
481s3 @ Doverbrook  Note:  Added 1.80 ft to the high chord b/c of curb (See survey drawings)
END DESCRIPTION:
Bridge Culvert--1,0,-1,-1, 0
Deck Dist Width WeirC Skew NumUp NumDn MinLoCord MaxHiCord MaxSubmerge Is_Ogee
35,37.1,2.6,0, 10, 11, , , .95, 0, 0,0,,
 1888.83 1943.54 1943.55  2001.6  2043.9 2104.45 2148.39  2148.4 2192.48 2643.13
    52.4   54.06   54.06   56.33   57.36   55.81   53.96   53.96   52.86   52.86
       0       0   50.96   53.23   54.26   52.71   50.86       0       0       0
 1828.67 1957.37 2012.08 2012.08 2070.14 2112.44 2172.99 2216.93 2216.93 2261.02
 2730.08
    52.4    52.4   54.06   54.06   56.33   57.36   55.81   53.96   53.96   52.86
   52.86
       0       0       0   50.96   53.23   54.26   52.71   50.86       0       0
       0
Pier Skew, UpSta & Num, DnSta & Num=  ,1984.54, 4 ,2053.08, 4 , 3 , 3 , 0 ,0,
    1.35    1.35       2       2
      25   50.06   50.06   54.26
    1.35    1.35       2       2
      25   50.06   50.06   54.26
Pier Skew, UpSta & Num, DnSta & Num=  ,2025.67, 4 ,2094.21, 4 , 3 , 3 , 0 ,0,
    1.35    1.35       2       2
      25    51.3    51.3   54.26
    1.35    1.35       2       2
      25    51.3    51.3   54.26
Pier Skew, UpSta & Num, DnSta & Num=  ,2066.63, 4 ,2135.17, 4 , 3 , 3 , 0 ,0,
    1.35    1.35       2       2
      25   51.15   51.15   54.26
    1.35    1.35       2       2
      25   51.15   51.15   54.26
Pier Skew, UpSta & Num, DnSta & Num=  ,2107.52, 4 ,2176.06, 4 , 3 , 3 , 0 ,0,
    1.35    1.35       2       2
      25   50.08   50.08   54.26
    1.35    1.35       2       2
      25   50.08   50.08   54.26
BR Coef=-1 , 0 , 0 ,, 0 ,,,.8,0,,0,
WSPro=,,,, 1 ,,,, 0 ,,,, 0 ,,,,-1 ,-1 ,-1 , 0 , 0 , 0 , 0 , 0
BC Design=,, 0 ,, 0 ,,,,,,

Type RM Length L Ch R = 1 ,18788.67,134.05,139.17,252.68
BEGIN DESCRIPTION:
481s3d,  XS 2/4 (surveyed)
Bank Station offset =      2886
END DESCRIPTION:
XS GIS Cut Line= 6
     3206273.283    13957284.774     3204715.026    13957887.222
     3204414.695    13958124.702     3204191.329    13958286.523
     3203650.715    13958379.256     3202559.774    13958553.898
#Sta/Elev= 30
       0   70.04  437.69   68.81   944.9   60.83  985.31   56.15 1027.09   59.95
 1083.96   60.43  1373.1   53.17  1599.3   56.52 1726.61   55.79 1798.01   54.91
 1940.24   48.88 2013.67   48.73 2091.61   46.59 2095.36   44.26  2097.7   40.41
 2113.77   29.91 2158.77   30.76 2173.77   33.01 2188.77   38.66 2218.77   42.41
 2242.15   45.51  2359.1   47.78 2438.08   48.08 2493.99   46.15 2861.19   57.27
 3064.95   56.08 3285.69   57.63 3624.77   67.39 3799.55   66.82 3984.02   70.14
#Mann= 3 , 0 , 0
       0     .12       0 2013.67     .06       0 2218.77     .12       0
#XS Ineff= 2 , 0
       0    2005    51.7    2220       0    51.8
Permanent Ineff=
       F       F
Bank Sta=2013.67,2218.77
XS Rating Curve= 0
Exp/Cntr=.5,.3

Type RM Length L Ch R = 1 ,18649.50,592.74,620.21,231.67
BEGIN DESCRIPTION:
481s3  XS 1/4, copy of 481s3d
Bank Station offset =      2122
Copied Survey setion adjusted to match slope between surveyed sections 481v20 and 481s3d, lowered by .28 ft
LOB Block and .01 Manning's to model Shook Gully, a dissimilar, studied stream.
END DESCRIPTION:
XS GIS Cut Line= 6
     3206622.602    13956381.201     3204715.026    13957717.222
     3204414.695    13957954.702     3204191.329    13958116.523
     3203650.715    13958209.256      3202515.72    13958445.458
#Sta/Elev= 30
       0   70.38  199.15   65.36  309.81   59.44  326.01    55.8  340.88    48.8
  351.65    47.6   414.4   58.48  583.54   63.19  788.21   66.24 1223.41   66.55
 1697.23   59.75 1766.31   56.32 2359.01   60.67 2562.71   54.51 2768.45   44.17
 2781.03   49.19 2855.62   46.31 2877.78   29.63 2922.78   30.48 2952.78   38.38
 3006.16   45.23 3095.85   46.51 3114.39      49 3319.55   45.85 3510.44   49.76
 3705.28   47.98 4266.81   64.32 4487.12      64 4554.59   68.01 4696.74      71
#Mann= 5 ,-1 , 0
       0     .12       0  199.15     .01       0  583.54     .12       0
 2855.62     .06       0 3006.16     .12       0
#Block Obstruct= 2 , 0
       0     585    63.1               0
Bank Sta=2855.62,3006.16
XS Rating Curve= 0
Exp/Cntr=.3,.1