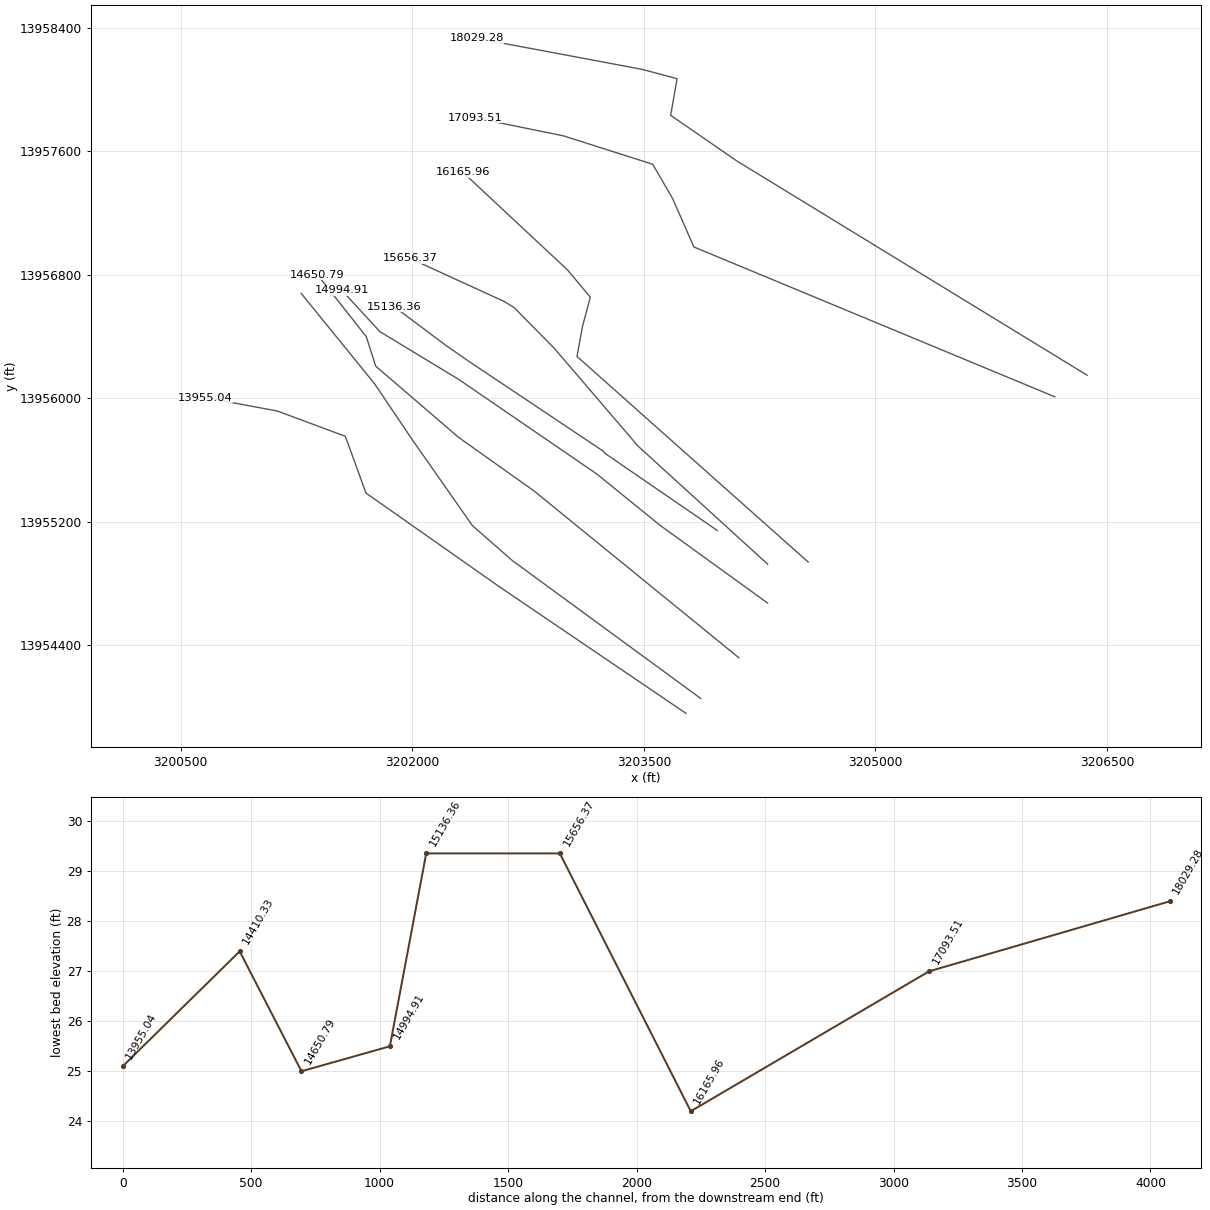
HEC-RAS study S100-00-00.prj: S100-00-00

--- S100-00-00.g02 (geometry) --- (continued)

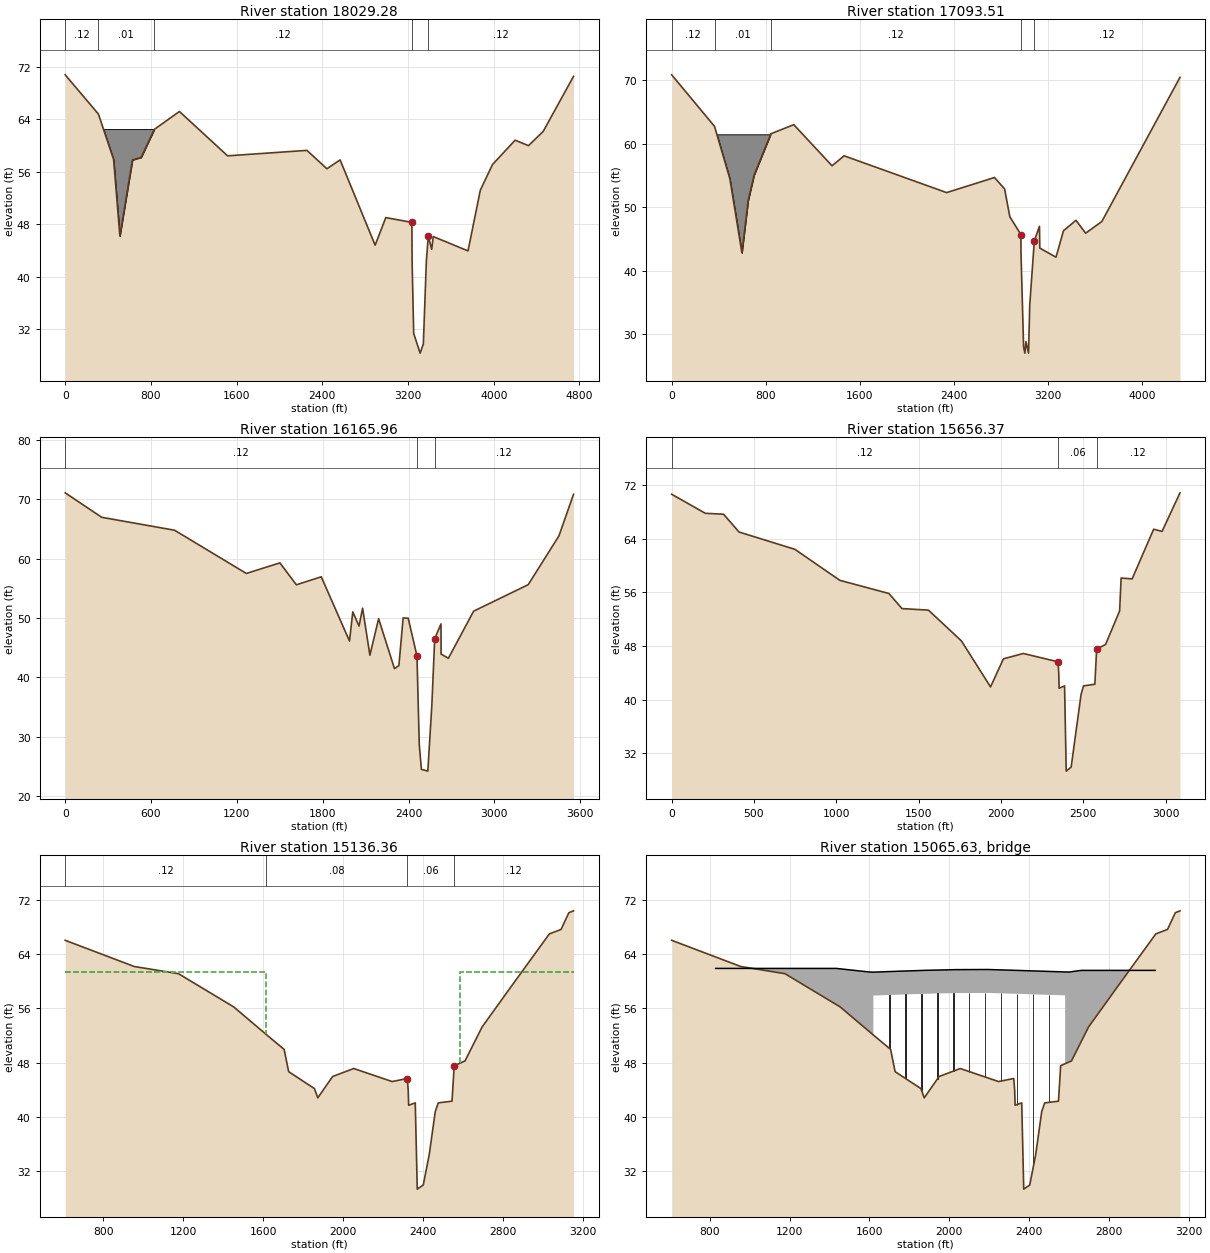
Type RM Length L Ch R = 1 ,18029.28,449.75,935.77,637.15
BEGIN DESCRIPTION:
481v20
Bank Station offset =      1687
LOB Block and .01 Manning's to model Shook Gully, a dissimilar, studied stream.
END DESCRIPTION:
XS GIS Cut Line= 6
     3206371.092    13956148.321     3204101.776    13957536.263
     3203673.753    13957831.684     3203715.191      13958068.6
     3203489.749    13958129.278     3202417.447    13958330.241
#Sta/Elev= 30
       0   70.76  309.94   64.79  451.78   57.88  510.52   46.22  628.06   57.81
  708.97   58.19   831.5   62.45 1066.26   65.18 1515.88   58.43 2256.55   59.26
 2442.91   56.46 2566.18   57.81 2893.15   44.83 2992.68   49.03 3236.18    48.3
 3238.18   42.37 3253.18    31.4 3313.18    28.4 3343.18    29.8 3371.18   42.37
 3389.18    46.2 3421.18    44.2 3435.84   46.14 3760.21   43.96 3875.23   53.21
 3989.07   57.11 4199.75   60.81 4324.82   59.98 4462.17   62.15 4745.13   70.53
#Mann= 5 ,-1 , 0
       0     .12       0  309.94     .01       0   831.5     .12       0
 3236.18     .06       0 3389.18     .12       0
#Block Obstruct= 2 , 0
       0     830    62.5               0
Bank Sta=3236.18,3389.18
XS Rating Curve= 0
Exp/Cntr=.3,.1

Type RM Length L Ch R = 1 ,17093.51,1054.92,927.55,790.19
BEGIN DESCRIPTION:
481v21  The ROB length differs by more than 20' from the channel length.
Bank Station offset =      1998
LOB Block and .01 Manning's to model Shook Gully, a dissimilar, studied stream.
END DESCRIPTION:
XS GIS Cut Line= 6
     3206161.501    13956008.594     3203824.087    13956978.927
     3203685.983    13957293.309     3203557.475    13957514.543
     3202978.634      13957698.8     3202407.281    13957815.151
#Sta/Elev= 30
       0   70.88  364.11   62.76  494.59    54.5  597.25   42.81  650.66   51.09
  700.73   55.08     843   61.58 1037.81   63.02 1363.05   56.54 1465.81   58.11
    2337   52.31 2743.81   54.69 2830.03   52.88 2874.24    48.5 2968.24    45.7
 2969.24   42.72 2991.24      28 3002.24      27 3011.24    28.8 3033.24      27
 3043.24    34.5 3082.24    44.7 3126.24      47 3128.94   43.56 3266.73   42.13
 3330.08   46.29 3436.39   47.94  3518.7   45.91 3656.22   47.75 4320.59   70.49
#Mann= 5 ,-1 , 0
       0     .12       0  364.11     .01       0     843     .12       0
 2968.24     .06       0 3082.24     .12       0
#Block Obstruct= 2 , 0
       0     850    61.5               0
Bank Sta=2968.24,3082.24
XS Rating Curve= 0
Exp/Cntr=.3,.1

Type RM Length L Ch R = 1 ,16165.96,289.13,509.59,507.69
BEGIN DESCRIPTION:
481v22 (also 483v5)  left side is Shook Gully.  Blocked area of Shook Gully main channel, as it will be conveying Shook
ilar and coincident peaks are not modeled.
Bank Station offset =      2465
END DESCRIPTION:
XS GIS Cut Line= 6
     3204564.426    13954938.199     3203066.919    13956269.959
     3203102.868    13956465.111     3203153.341    13956653.655
     3203005.714    13956830.179     3202328.956    13957461.915
#Sta/Elev= 30
       0   71.07  255.02   66.95  764.56   64.77 1266.25   57.49 1500.93   59.27
 1615.98   55.58 1790.01   56.93 1987.42   46.11  2010.5   51.02 2053.96   48.63
 2079.06   51.64 2130.03   43.72 2191.09   49.87 2301.73   41.47 2332.73   41.97
 2362.42      50 2397.68   49.96 2459.09    43.6 2475.09    28.7 2490.09    24.5
 2535.09    24.2 2563.09    35.3 2583.09    46.5 2627.09      49  2627.8   43.92
 2678.57    43.2 2855.14   51.14 3236.75    55.6 3451.91   63.83  3553.6   70.83
#Mann= 3 , 0 , 0
       0     .12       0 2459.09     .06       0 2583.09     .12       0
Bank Sta=2459.09,2583.09
XS Rating Curve= 0
Exp/Cntr=.3,.1

Type RM Length L Ch R = 1 ,15656.37,434.08,520.01,434
BEGIN DESCRIPTION:
481s2, XS 4/4, copy of 481s2u, adjust invert as needed based on data from nearest surveyed sections.  Blocked area of Sh
surface.  The Shook and Luce drainage areas are dissimilar and coincident peaks are not modeled.
Bank Station offset =      2603
END DESCRIPTION:
XS GIS Cut Line= 6
     3204301.613    13954924.659     3203462.279     13955689.28
     3202922.498    13956319.629     3202659.065    13956587.089
     3202596.456    13956625.462     3201984.144    13956905.915
#Sta/Elev= 30
       0   70.62  204.32   67.78  315.32   67.64  409.18   64.99  748.79   62.41
 1021.49   57.79 1319.55   55.83 1399.05   53.58 1559.97   53.35 1760.14   48.76
 1936.99   41.91 2015.31   46.09  2136.1   46.89 2346.85   45.65 2351.46   43.92
 2353.68   41.71 2386.78   42.06 2396.78   29.36 2426.78   29.96 2486.78   40.76
 2501.78   42.06 2570.73   42.31  2581.6   47.54 2635.67   48.23 2721.17   53.23
 2730.43   58.13 2797.29   58.01 2927.97   65.41    2979   65.08 3087.96   70.83
#Mann= 3 , 0 , 0
       0     .12       0 2346.85     .06       0  2581.6     .12       0
Bank Sta=2346.85,2581.6
XS Rating Curve= 0
Exp/Cntr=.5,.3

Type RM Length L Ch R = 1 ,15136.36,158.08,141.46,142.99
BEGIN DESCRIPTION:
481s2u, XS 3/4
Bank Station offset =      3458
XS and Bridge stations shifted 830' to align channels
END DESCRIPTION:
XS GIS Cut Line= 6
 3203975.421341813955142.9220801     3203253.815    13955638.403
     3203233.898     13955658.32     3202355.068    13956245.866
     3202215.651    13956342.961     3201884.704    13956590.788
#Sta/Elev= 30
     610      66  955.72   62.14  1177.1   61.08 1452.88    56.2 1615.05   52.16
 1705.89   49.93 1728.18   46.66 1857.43   44.16 1874.12    42.8 1948.29   45.94
 2054.03   47.12  2246.1    45.2 2322.02   45.65 2326.63   43.92 2328.85   41.71
 2361.95   42.06 2371.95   29.36 2401.95   29.96 2431.95   34.46 2461.95   40.76
 2476.95   42.06  2545.9   42.31 2556.77   47.54 2610.84   48.23 2696.34   53.23
 2840.21   59.12 3032.98   66.94 3091.63    67.6 3130.64   70.06 3154.02   70.34
#Mann= 4 ,-1 , 0
     610     .12       0 1615.05     .08       0 2322.02     .06       0
 2556.77     .12       0
#XS Ineff= 2 , 0
       0    1615   61.31    2585       0   61.33
Permanent Ineff=
       F       F
Bank Sta=2322.02,2556.77
XS Rating Curve= 0
Exp/Cntr=.5,.3

Type RM Length L Ch R = 3 ,15065.63,,,
BEGIN DESCRIPTION:
Humble - Crosby (FM 2100)  481s2
END DESCRIPTION:
Bridge Culvert--1,0,-1,-1, 0
Deck Dist Width WeirC Skew NumUp NumDn MinLoCord MaxHiCord MaxSubmerge Is_Ogee
49,43,2.6,0, 16, 16, , , .95, 0, 0,0,,
  830.02 1434.45 1599.49 1619.42 1619.52 1730.02 1881.99 2031.88 2192.95 2359.38
 2494.25 2579.11 2579.12 2599.28 2659.77 3030.02
   61.86   61.86   61.33   61.31   61.31   61.43   61.58   61.68    61.7   61.55
   61.42   61.34   61.34   61.33   61.57   61.57
       0       0       0       0   57.86   57.98   58.13   58.23   58.25    58.1
   57.97   57.89       0       0       0       0
  664.58 1432.01 1597.05 1616.98 1617.08 1727.58 1879.55 2029.44 2190.51 2356.94
 2491.81 2576.67 2576.68 2596.84 2657.33 3027.58
   61.86   61.86   61.33   61.31   61.31   61.43   61.58   61.68    61.7   61.55
   61.42   61.34   61.34   61.33   61.57   61.57
       0       0       0       0   57.86   57.98   58.13   58.23   58.25    58.1
   57.97   57.89       0       0       0       0
Pier Skew, UpSta & Num, DnSta & Num=  ,1699.63, 4 ,1697.19, 4 , 3 , 3 , 0 ,0,
       2       2     2.5     2.5
      25   55.41   55.41   58.41
       2       2     2.5     2.5
      25   55.41   55.41   58.41
Pier Skew, UpSta & Num, DnSta & Num=  ,1779.38, 4 ,1776.94, 4 , 3 , 3 , 0 ,0,
       2       2     2.5     2.5
      25   55.41   55.41   58.41
       2       2     2.5     2.5
      25   55.41   55.41   58.41
Pier Skew, UpSta & Num, DnSta & Num=  ,1859.3, 4 ,1856.86, 4 , 3 , 3 , 0 ,0,
       2       2     2.5     2.5
      25   55.41   55.41   58.41
       2       2     2.5     2.5
      25   55.41   55.41   58.41
Pier Skew, UpSta & Num, DnSta & Num=  ,1939.28, 4 ,1938.84, 4 , 3 , 3 , 0 ,0,
       2       2     2.5     2.5
      25   55.41   55.41   58.41
       2       2     2.5     2.5
      25   55.41   55.41   58.41
Pier Skew, UpSta & Num, DnSta & Num=  ,2019.32, 4 ,2016.88, 4 , 3 , 3 , 0 ,0,
       2       2     2.5     2.5
      25   55.41   55.41   58.41
       2       2     2.5     2.5
      25   55.41   55.41   58.41
Pier Skew, UpSta & Num, DnSta & Num=  ,2099.13, 4 ,2096.69, 4 , 3 , 3 , 0 ,0,
       2       2     2.5     2.5
      25   55.41   55.41   58.41
       2       2     2.5     2.5
      25   55.41   55.41   58.41
Pier Skew, UpSta & Num, DnSta & Num=  ,2178.91, 4 ,2176.47, 4 , 3 , 3 , 0 ,0,
       2       2     2.5     2.5
      25   55.41   55.41   58.41
       2       2     2.5     2.5
      25   55.41   55.41   58.41
Pier Skew, UpSta & Num, DnSta & Num=  ,2259.06, 4 ,2256.62, 4 , 3 , 3 , 0 ,0,
       2       2     2.5     2.5
      25   55.41   55.41   58.41
       2       2     2.5     2.5
      25   55.41   55.41   58.41
Pier Skew, UpSta & Num, DnSta & Num=  ,2339.09, 4 ,2336.65, 4 , 3 , 3 , 0 ,0,
       2       2     2.5     2.5
      25   55.41   55.41   58.41
       2       2     2.5     2.5
      25   55.41   55.41   58.41
Pier Skew, UpSta & Num, DnSta & Num=  ,2419.14, 4 ,2416.7, 4 , 3 , 3 , 0 ,0,
       2       2     2.5     2.5
      25   55.41   55.41   58.41
       2       2     2.5     2.5
      25   55.41   55.41   58.41
Pier Skew, UpSta & Num, DnSta & Num=  ,2499.02, 4 ,2496.58, 4 , 3 , 3 , 0 ,0,
       2       2     2.5     2.5
      25   55.41   55.41   58.41
       2       2     2.5     2.5
      25   55.41   55.41   58.41
BR Coef=-1 , 0 , 0 ,, 0 ,,,.8,0,,0,
WSPro=,,,, 1 ,,,, 0 ,,,, 0 ,,,,-1 ,-1 ,-1 , 0 , 0 , 0 , 0 , 0
BC Design=,, 0 ,, 0 ,,,,,,

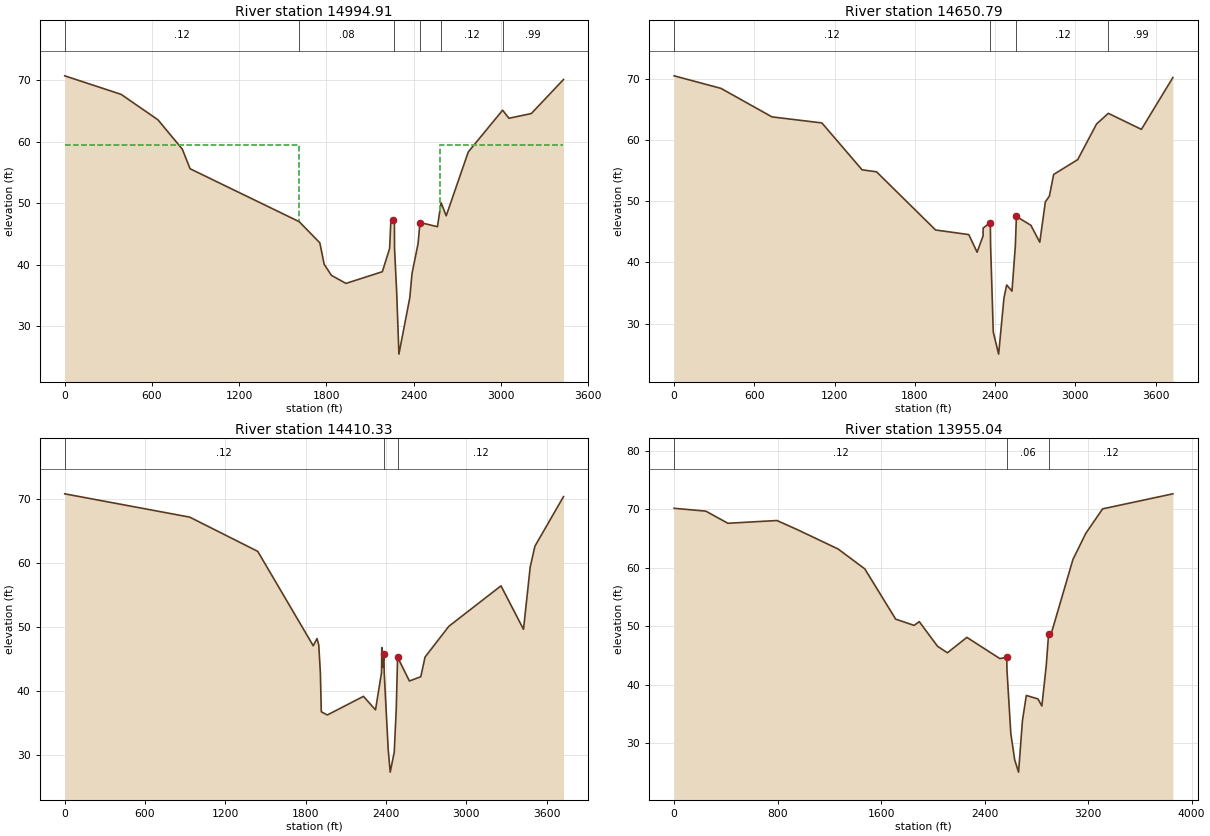
Type RM Length L Ch R = 1 ,14994.91,314.85,344.12,270.14
BEGIN DESCRIPTION:
481v23, XS 2/4 of 481s2
Bank Station offset =      2686
END DESCRIPTION:
XS GIS Cut Line= 6
     3204301.613    13954672.499     3203604.261    13955176.639
     3203194.646    13955508.927      3202300.36    13956121.571
     3201789.978    13956430.729     3201545.271    13956697.116
#Sta/Elev= 30
       0   70.75  387.65   67.74  641.24    63.6  808.77   58.83  862.38   55.64
 1612.51   47.04 1754.58    43.6 1784.58    40.1 1834.58    38.3 1934.58      37
 2184.58    38.9 2234.58   42.67 2242.58    46.8 2259.58    47.3 2267.58    46.7
 2268.58   42.67 2283.58    35.4 2298.58    25.5 2373.58    34.7 2388.58    38.6
 2430.58    43.5 2443.58    46.9 2563.49   46.22 2588.76   50.12 2623.84   47.99
 2775.82   58.38  3011.9   65.16 3055.37   63.85 3209.43   64.62 3430.53   70.15
#Mann= 6 ,-1 , 0
       0     .12       0 1612.51     .08       0 2267.58     .06       0
 2443.58     .08       0 2588.76     .12       0  3011.9     .99       0
#XS Ineff= 2 , 0
       0    1610    59.5    2580       0    59.5
Permanent Ineff=
       F       F
Bank Sta=2259.58,2443.58
XS Rating Curve= 0
Exp/Cntr=.5,.3

Type RM Length L Ch R = 1 ,14650.79,443.84,240.45,151.38
BEGIN DESCRIPTION:
481v24, XS 1/4 of 481s2
Bank Station offset =      2573
END DESCRIPTION:
XS GIS Cut Line= 6
     3204115.495    13954318.275      3202788.17    13955399.136
     3202300.027    13955745.831     3201763.379    13956206.877
     3201702.037    13956398.579     3201385.779    13956799.355
#Sta/Elev= 30
       0   70.49  350.34   68.44  731.51   63.78 1104.89   62.79 1405.59   55.13
 1513.77    54.8 1955.32   45.29 2203.49   44.54 2265.69   41.66 2310.47   44.33
  2310.7    45.6  2364.7    46.5  2366.7   42.69  2386.7    28.6  2426.7      25
  2466.7    34.2  2486.7    36.3  2526.7    35.3  2551.7   42.69  2559.7    47.5
 2667.82   46.06  2734.4   43.29 2776.21   49.89  2806.2   50.82 2838.24   54.37
    3018   56.79 3159.16   62.62 3247.22   64.36  3494.3   61.74 3729.81   70.21
#Mann= 4 ,-1 , 0
       0     .12       0  2364.7     .06       0  2559.7     .12       0
 3247.22     .99       0
Bank Sta=2364.7,2559.7
XS Rating Curve= 0
Exp/Cntr=.3,.1

Type RM Length L Ch R = 1 ,14410.33,219.15,455.29,360.82
BEGIN DESCRIPTION:
481v25
Bank Station offset =      2568
END DESCRIPTION:
XS GIS Cut Line= 6
     3203869.339    13954054.107     3202647.553    13954948.376
     3202389.611    13955174.152     3201997.861    13955733.795
     3201755.138    13956093.927     3201280.814    13956678.031
#Sta/Elev= 30
       0   70.74  934.11   67.11 1442.26   61.78 1856.89   47.08 1885.12    48.2
 1898.12    47.2 1910.12    42.9 1917.12    36.8 1962.12    36.3 2232.12    39.2
 2322.12    37.1 2367.12    42.9 2369.12    46.8 2374.62    43.7 2385.12    45.8
 2387.12    42.9 2417.12    30.9 2432.12    27.4 2462.12    30.5 2477.12    37.2
 2487.12    45.3 2575.62   41.59 2660.43   42.26 2692.47   45.32 2869.99   50.11
 3259.82   56.41 3427.98   49.64 3478.03   59.34 3513.39   62.59 3726.76    70.3
#Mann= 3 , 0 , 0
       0     .12       0 2385.12     .06       0 2487.12     .12       0
Bank Sta=2385.12,2487.12
XS Rating Curve= 0
Exp/Cntr=.3,.1

Type RM Length L Ch R = 1 ,13955.04,140.87,493.85,768.16
BEGIN DESCRIPTION:
481v26
Bank Station offset =      2338
END DESCRIPTION:
XS GIS Cut Line= 6
     3203773.278    13953958.046     3202570.554    13954773.927
     3201700.236     13955385.03       3201566.6    13955752.485
      3201126.34      13955916.3     3200658.233    13956003.832
#Sta/Elev= 30
       0   70.17  245.28   69.68  415.45   67.61  794.76   68.08  952.56   66.52
 1267.22   63.22 1473.66   59.82  1712.5   51.23 1854.82   50.17 1894.76   50.81
 2035.85    46.6 2112.52   45.49 2262.68   48.12 2517.21    44.5 2571.21    44.7
 2572.21   42.68 2602.21    31.7 2632.21    27.2 2662.21    25.1 2692.21    33.9
 2722.21    38.2 2812.21    37.6 2842.21    36.4 2876.21    43.3 2894.21    48.7
 2919.21    49.1 3082.76   61.45 3181.96   65.89 3311.57   70.07 3854.89   72.64
#Mann= 3 , 0 , 0
       0     .12       0 2571.21     .06       0 2894.21     .12       0
Bank Sta=2571.21,2894.21
XS Rating Curve= 0
Exp/Cntr=.3,.1