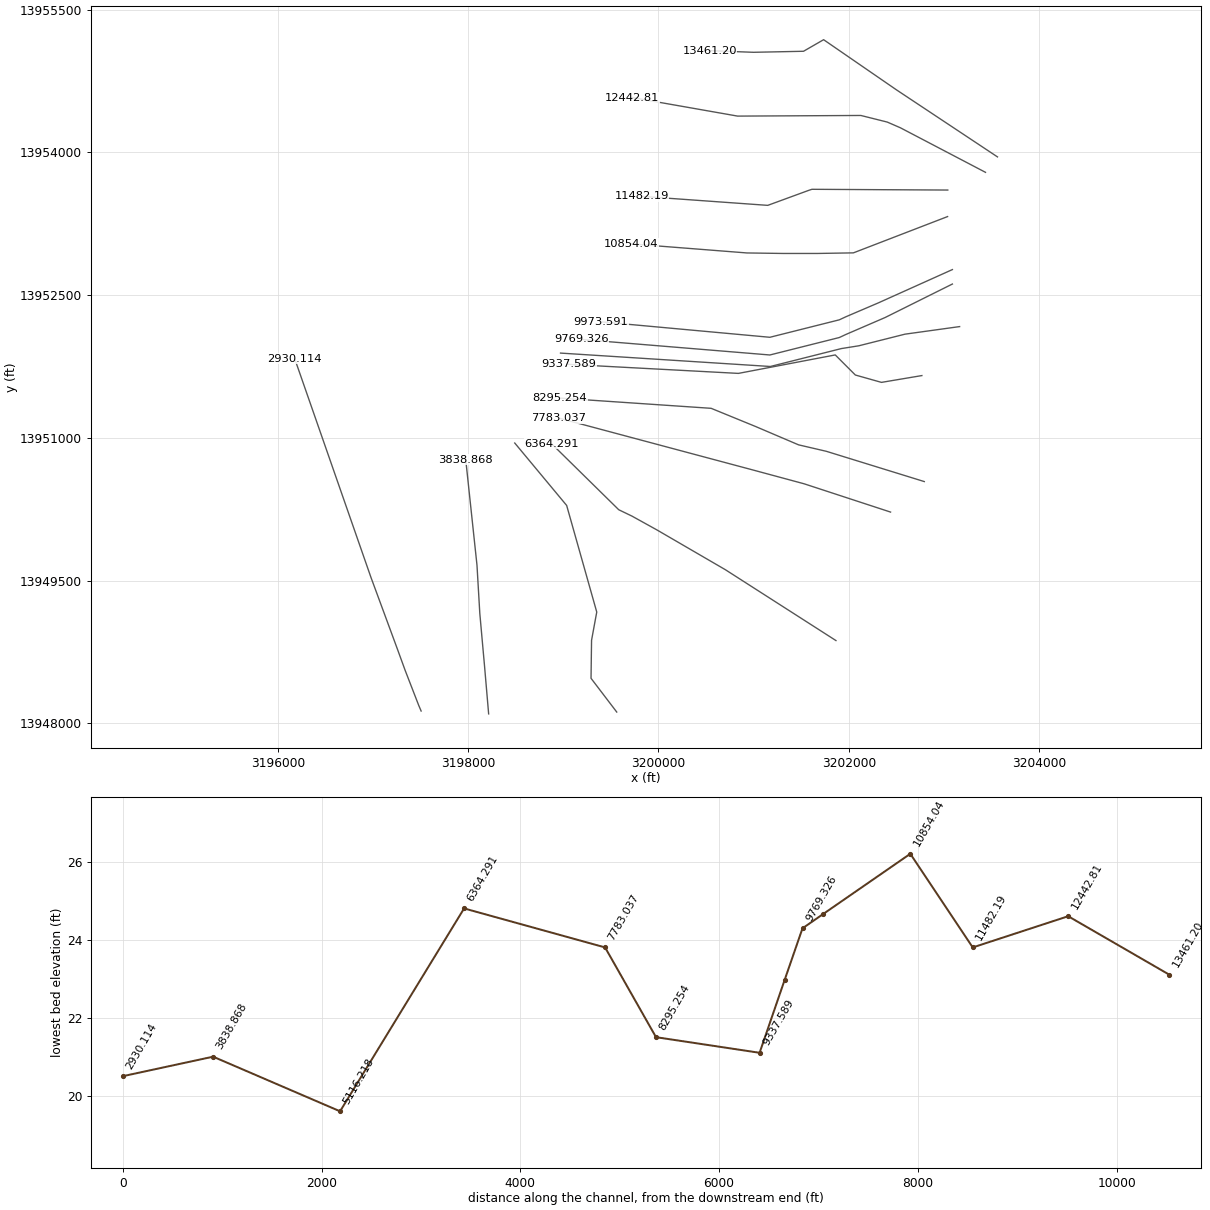
HEC-RAS study S100-00-00.prj: S100-00-00

--- S100-00-00.g02 (geometry) --- (continued)

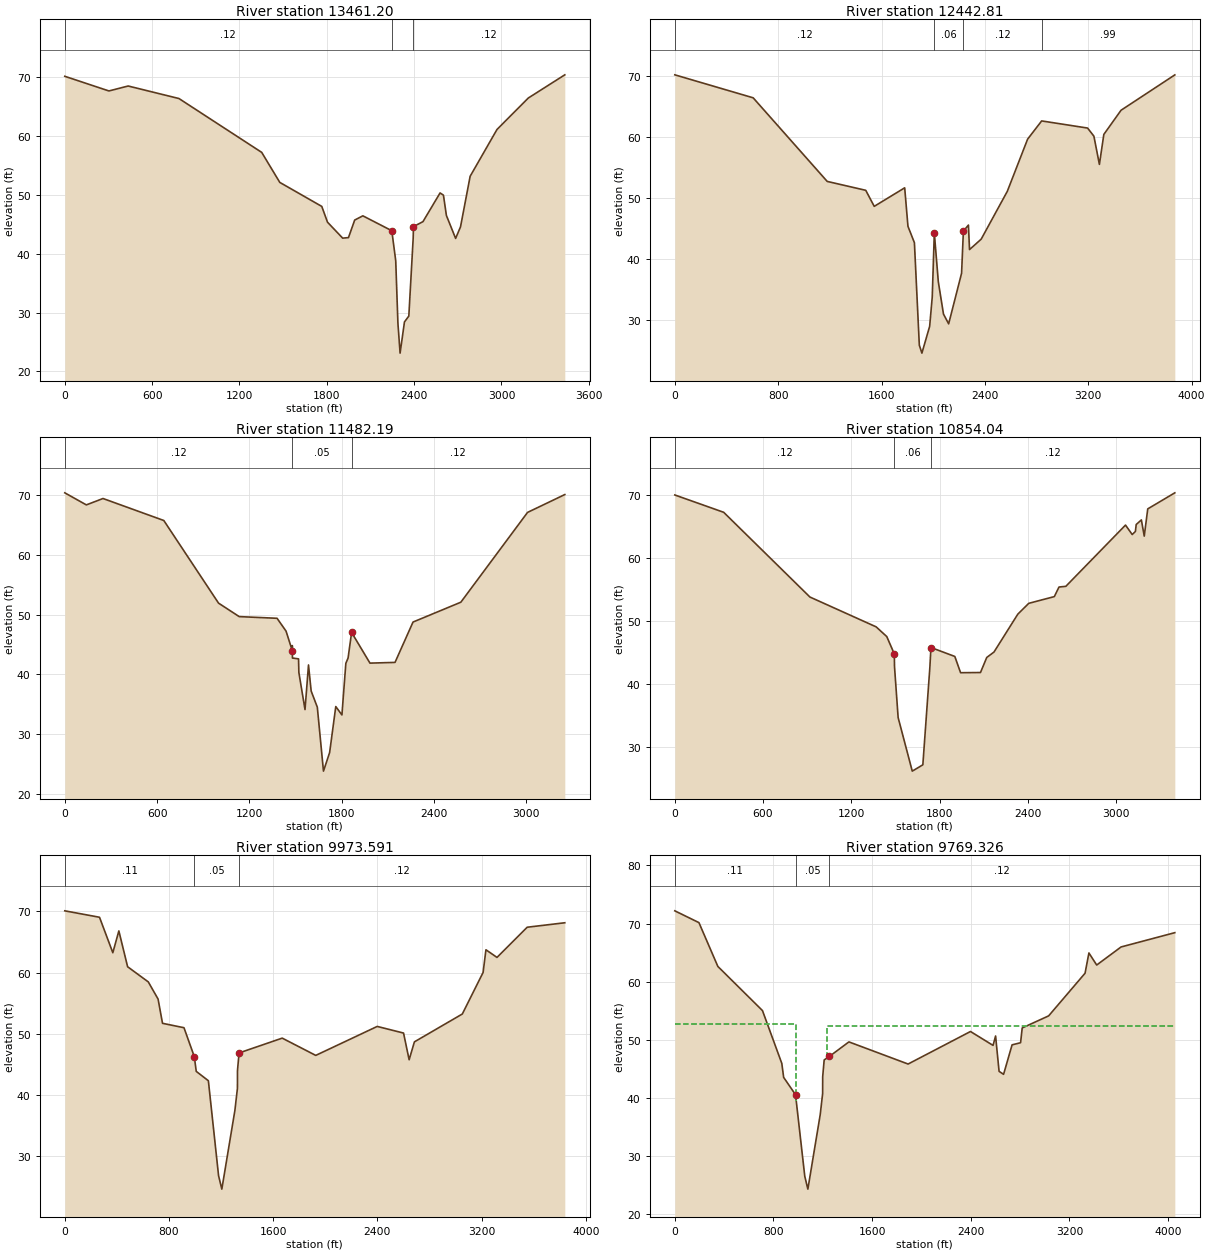
Type RM Length L Ch R = 1 ,13461.20,699.55,1018.39,779.41
BEGIN DESCRIPTION:
481v27
Bank Station offset =      2696
END DESCRIPTION:
XS GIS Cut Line= 6
     3203563.145    13953952.043     3202503.233    13954655.545
     3201735.622    13955184.026     3201524.528    13955062.279
     3200998.379     13955051.55     3200537.227     13955068.75
#Sta/Elev= 30
       0   70.14  303.38   67.65  435.49   68.49  784.51   66.36 1353.06   57.21
 1477.24   52.11 1765.74   48.03 1805.04   45.35 1909.24   42.64 1949.19   42.73
 1991.84   45.71 2047.93   46.43 2246.82    43.9 2273.82    38.8 2288.82    28.2
 2303.82    23.1 2333.82    28.4 2363.82    29.4 2393.82   42.68 2395.82    44.6
 2460.96   45.44 2578.48   50.32 2601.69   49.94 2621.89    46.5 2685.28   42.59
 2718.97   44.56 2785.09   53.15 2969.73   61.11 3184.78   66.45  3435.5   70.39
#Mann= 3 , 0 , 0
       0     .12       0 2246.82     .06       0 2395.82     .12       0
Bank Sta=2246.82,2395.82
XS Rating Curve= 0
Exp/Cntr=.3,.1

Type RM Length L Ch R = 1 ,12442.81,795.06,960.61,966.03
BEGIN DESCRIPTION:
481v28
Bank Station offset =      3088
END DESCRIPTION:
XS GIS Cut Line= 6
     3203437.065     13953789.94     3202542.498    13954258.237
      3202404.41    13954318.275     3202126.806    13954387.683
     3200832.179    13954380.927     3199720.709    13954576.438
#Sta/Elev= 30
       0   70.24  606.41   66.47 1179.48   52.76 1477.76    51.3 1543.47   48.67
 1779.16   51.71 1804.41    45.4 1854.41   42.71 1892.41    25.9 1912.41    24.6
 1972.41      29 1992.41    33.8 2008.41    44.3 2039.41    36.3 2079.41      31
 2119.41    29.4 2219.41    37.7 2233.41    44.6 2272.41    45.6 2280.91   41.58
 2371.18   43.29 2573.24   51.13 2730.47   59.69 2839.16   62.68 3194.71   61.51
 3243.45   60.18 3286.09   55.55 3320.44   60.47 3453.62   64.43 3869.78   70.23
#Mann= 4 ,-1 , 0
       0     .12       0 2008.41     .06       0 2233.41     .12       0
 2839.16     .99       0
Bank Sta=2008.41,2233.41
XS Rating Curve= 0
Exp/Cntr=.3,.1

Type RM Length L Ch R = 1 ,11482.19,696.65,628.16,523.41
BEGIN DESCRIPTION:
481v29
Bank Station offset =      3318
END DESCRIPTION:
XS GIS Cut Line= 5
     3203040.814    13953603.822     3201612.701    13953611.626
     3201580.648    13953601.138     3201148.707    13953442.901
     3199822.774     13953537.78
#Sta/Elev= 30
       0   70.36  140.21   68.34   248.5   69.41  643.85   65.73   999.6   51.91
 1134.17   49.65 1380.27   49.37 1438.73   47.22 1479.29   43.94 1479.29    44.8
 1480.29   42.72 1519.94   42.58 1521.99    40.3 1561.99    34.1 1584.64   41.56
 1601.99    37.2 1641.99    34.5 1681.99    23.8 1721.99    26.9 1761.99    34.6
 1801.99    33.2 1827.47   41.83 1841.99   42.72 1864.99      47 1984.39   41.87
 2147.27   41.99  2264.3   48.74 2575.23   52.06 3008.85   67.08  3251.2   70.07
#Mann= 3 , 0 , 0
       0     .12       0 1479.29     .05       0 1864.99     .12       0
Bank Sta=1479.29,1864.99
XS Rating Curve= 0
Exp/Cntr=.3,.1

Type RM Length L Ch R = 1 ,10854.04,881,880.45,880
BEGIN DESCRIPTION:
481v30
Bank Station offset =      3385
END DESCRIPTION:
XS GIS Cut Line= 6
     3203038.482    13953325.043     3202048.538    13952943.609
     3201668.243    13952937.334     3201310.247    13952937.375
     3200930.271     13952942.71     3199713.323    13953038.101
#Sta/Elev= 30
       0   70.03  332.35   67.28  918.83   53.83 1368.86    49.1 1441.23   47.56
 1492.57    44.8 1493.97   42.76 1518.57    34.7 1614.57    26.2 1686.57    27.2
 1734.57   42.76 1741.57   45.82    1904    44.4 1943.22   41.82 2078.47   41.85
  2121.1   44.24 2170.33    45.1 2332.25   51.11 2406.65   52.83 2580.67    53.9
 2612.33   55.42 2658.86   55.53 3064.62   65.25 3110.16   63.75 3131.86   64.24
 3137.32   65.34 3172.45   66.07 3192.04    63.5 3215.81   67.82 3399.92   70.37
#Mann= 3 , 0 , 0
       0     .12       0 1492.57     .06       0 1741.57     .12       0
Bank Sta=1492.57,1741.57
XS Rating Curve= 0
Exp/Cntr=.3,.1

Type RM Length L Ch R = 1 ,9973.591,170.85,204.26,183.38
BEGIN DESCRIPTION:
481s1, XS 4/4, copy of 481s1u
Bank Station offset =      3794
Copied Survey setion adjusted to match slope between surveyed sections 481v30 and 481s1u, raised by .36 ft
END DESCRIPTION:
XS GIS Cut Line= 6
     3203089.119    13952768.037     3202311.708     13952418.35
     3201968.263    13952271.443     3201900.682    13952239.895
     3201170.845    13952056.416     3199392.622     13952219.47
#Sta/Elev= 30
       0    70.1  266.56   69.05  368.83   63.26  415.07   66.82  482.28   60.97
  641.11   58.49  716.21   55.69  750.25   51.73  915.14   51.01  994.26   46.29
 1009.27   43.88 1102.37   42.35 1180.59   26.85 1205.59   24.65 1305.59   37.45
 1325.42    41.1 1325.85   44.01 1337.93   46.89 1669.28   49.31 1926.75   46.49
 2398.68   51.22 2600.71   50.14 2643.75   45.78 2684.15    48.7 3052.08   53.25
 3211.63   60.04 3233.36   63.74 3318.21   62.49 3549.92   67.42 3838.83   68.15
#Mann= 3 , 0 , 0
       0     .11       0  994.26     .05       0 1337.93     .12       0
Bank Sta=994.26,1337.93
XS Rating Curve= 0
Exp/Cntr=.5,.3

Type RM Length L Ch R = 1 ,9769.326,239.47,180.69,122.45
BEGIN DESCRIPTION:
481s1u, XS3/4
Bank Station offset =      3921
END DESCRIPTION:
XS GIS Cut Line= 6
     3203089.119    13952616.126     3202382.184    13952264.113
     3201968.263    13952085.443     3201900.682    13952053.895
     3201170.845    13951870.416     3199190.074    13952033.801
#Sta/Elev= 30
       0   72.19  195.72   70.16   349.1   62.62  710.94   55.02  867.82   45.93
  882.83   43.52  979.15   40.54 1054.15   26.49 1079.15   24.29 1179.15   37.09
 1198.98   40.74 1199.41   43.65 1211.49   46.53 1254.49   47.14 1412.05   49.63
 1892.02   45.82 2398.06   51.42 2580.99   49.03 2601.62   50.65 2629.92   44.56
 2666.48   44.05 2735.28   49.12 2804.38   49.49 2817.44   52.03    3032   54.11
 3327.27   61.45 3358.56   64.94 3421.65   62.86 3619.26   65.97 4055.24   68.43
#Mann= 3 , 0 , 0
       0     .11       0  979.15     .05       0 1254.49     .12       0
#XS Ineff= 2 , 0
       0     985    52.7    1235       0   52.34
Permanent Ineff=
       F       F
Bank Sta=979.15,1254.49
XS Rating Curve= 0
Exp/Cntr=.5,.3

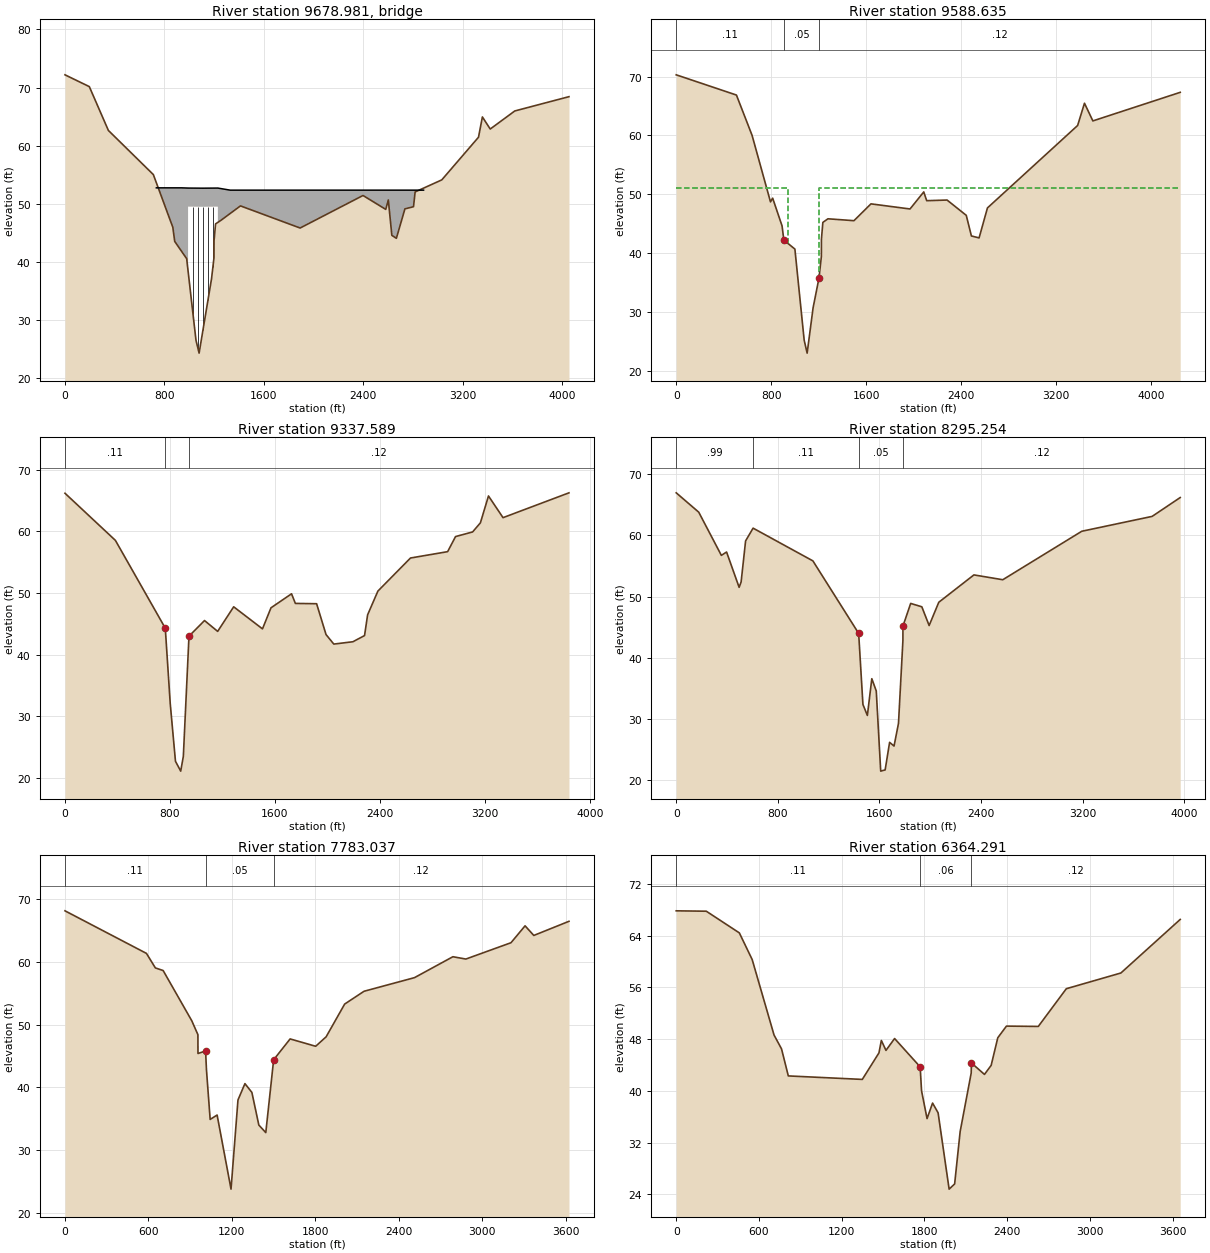
Type RM Length L Ch R = 3 ,9678.981,,,
BEGIN DESCRIPTION:
FM 1485 Huffman - Cleveland    481s1
END DESCRIPTION:
Bridge Culvert--1,0,-1,-1, 0
Deck Dist Width WeirC Skew NumUp NumDn MinLoCord MaxHiCord MaxSubmerge Is_Ogee
77.25,25.5,2.6,0, 9, 9, , , .95, 0, 0,0,,
  735.15  936.65  990.35  990.45 1110.15 1230.05 1230.15 1329.75 2885.15
   52.74   52.74    52.7    52.7   52.68    52.7    52.7   52.34   52.34
      40      40       0    49.5   49.48    49.5       0      40      30
  696.68  898.18  951.88  951.98 1071.68 1191.58 1191.68 1291.28    2855
   52.74   52.74    52.7    52.7   52.68    52.7    52.7   52.34   52.34
      40      40       0    49.5   49.48    49.5       0      40      30
Pier Skew, UpSta & Num, DnSta & Num=  ,1030.15, 4 ,991.68, 4 , 3 , 3 , 0 ,0,
    1.35    1.35       2       2
      20   47.54   47.54   49.54
    1.35    1.35       2       2
      20   47.54   47.54   49.54
Pier Skew, UpSta & Num, DnSta & Num=  ,1070.15, 4 ,1031.68, 4 , 3 , 3 , 0 ,0,
    1.35    1.35       2       2
      20   47.54   47.54   49.54
    1.35    1.35       2       2
      20   47.54   47.54   49.54
Pier Skew, UpSta & Num, DnSta & Num=  ,1110.15, 4 ,1071.68, 4 , 3 , 3 , 0 ,0,
    1.35    1.35       2       2
      20   47.54   47.54   49.54
    1.35    1.35       2       2
      20   47.54   47.54   49.54
Pier Skew, UpSta & Num, DnSta & Num=  ,1150.15, 4 ,1111.68, 4 , 3 , 3 , 0 ,0,
    1.35    1.35       2       2
      20   47.54   47.54   49.54
    1.35    1.35       2       2
      20   47.54   47.54   49.54
Pier Skew, UpSta & Num, DnSta & Num=  ,1190.15, 4 ,1151.68, 4 , 3 , 3 , 0 ,0,
    1.35    1.35       2       2
      20   47.54   47.54   49.54
    1.35    1.35       2       2
      20   47.54   47.54   49.54
BR Coef=-1 , 0 , 0 ,, 0 ,,,.8,0,,0,
WSPro=,,,, 1 ,,,, 0 ,,,, 0 ,,,,-1 ,-1 ,-1 , 0 , 0 , 0 , 0 , 0
BC Design=,, 1 ,20, 0 ,,,,,,

Type RM Length L Ch R = 1 ,9588.635,477.38,251.05,36.3
BEGIN DESCRIPTION:
481s1, XS 2/4, copy of 481s1u
Bank Station offset =      3897
Copied Survey setion adjusted to match slope between surveyed sections 481v31 and 481s1u, lowered by 1.33 ft
END DESCRIPTION:
XS GIS Cut Line= 6
     3203165.075    13952168.833     3202591.318    13952089.258
     3202105.666    13951967.041     3201922.229    13951937.761
     3201175.965    13951749.473     3198970.648     13951890.33
#Sta/Elev= 30
       0    70.3  507.29   66.86  639.11      60  794.18   48.69  812.55   49.32
  891.67    44.6  906.68   42.19  999.78   40.66    1078   25.16    1103   22.96
    1153   30.66    1203   35.76 1222.83   39.41 1223.26   42.32 1235.34    45.2
 1278.34   45.81 1497.39   45.49 1640.64   48.35 1969.69   47.48 2085.42   50.38
 2110.21   48.89 2281.86      49 2443.47    46.4 2486.82   42.89 2551.58   42.56
 2622.05   47.66 3381.75   61.68  3439.5   65.47 3510.14   62.46 4246.05   67.32
#Mann= 3 , 0 , 0
       0     .11       0  906.68     .05       0    1203     .12       0
#XS Ineff= 2 , 0
       0     945    51.1    1200       0    51.1
Permanent Ineff=
       F       F
Bank Sta=906.68,1203
XS Rating Curve= 0
Exp/Cntr=.5,.3

Type RM Length L Ch R = 1 ,9337.589,997.93,1042.33,663.07
BEGIN DESCRIPTION:
481v31, XS 1/4 of 481s1
Bank Station offset =      4118
END DESCRIPTION:
XS GIS Cut Line= 6
     3202768.419    13951654.024     3202343.693    13951582.484
     3202069.148    13951659.889     3201858.054    13951870.982
     3200840.209    13951676.906     3199055.042    13951772.177
#Sta/Elev= 30
       0    66.2  384.15   58.55  764.18    44.3  801.78    32.1  841.78    22.7
  881.78    21.1  901.78    23.5  944.78      43 1063.15   45.54 1163.31   43.78
 1285.34   47.77  1504.8   44.19  1569.7   47.61 1726.18   49.88 1755.44   48.32
 1917.23   48.27 1988.93   43.27  2048.2   41.72 2193.75    42.1 2282.34    43.1
 2305.88   46.47 2384.15   50.32 2632.52   55.69 2915.48   56.72 2975.76   59.17
 3105.78   59.92 3165.17    61.4 3226.73   65.76 3337.65   62.24 3840.08   66.27
#Mann= 3 ,-1 , 0
       0     .11       0  764.18     .05       0  944.78     .12       0
Bank Sta=764.18,944.78
XS Rating Curve= 0
Exp/Cntr=.3,.1

Type RM Length L Ch R = 1 ,8295.254,412.58,512.22,481.28
BEGIN DESCRIPTION:
481v32
Bank Station offset =      3390
LOB .99 used for ineffective flow due to part of a laterial stream.  Can be used for storage.
END DESCRIPTION:
XS GIS Cut Line= 6
     3202793.737    13950540.011     3201764.254    13950858.052
     3201472.369    13950926.003     3201017.506    13951120.068
     3200553.639    13951309.852     3198962.208    13951417.718
#Sta/Elev= 30
       0   66.97  177.17   63.81  355.39   56.75  396.42    57.3  495.23   51.53
  510.93   52.41  546.15   59.11  605.13    61.2 1076.02   55.85 1436.41      44
 1469.91    32.4 1504.91    30.6 1539.91    36.6 1574.91    34.6 1609.91    21.5
 1644.91    21.7 1679.91    26.2 1714.91    25.6 1749.91    29.3 1784.61   42.78
 1785.11    45.2 1845.91    48.9 1933.61   48.35 1991.24   45.29 2067.18   49.09
 2343.81   53.56 2570.97   52.77 3193.02   60.69 3746.91   63.12 3967.99    66.2
#Mann= 4 ,-1 , 0
       0     .99       0  605.13     .11       0 1436.41     .05       0
 1785.11     .12       0
Bank Sta=1436.41,1785.11
XS Rating Curve= 0
Exp/Cntr=.3,.1

Type RM Length L Ch R = 1 ,7783.037,1382.07,1418.75,1007.69
BEGIN DESCRIPTION:
481v33
Bank Station offset =      3806
END DESCRIPTION:
XS GIS Cut Line= 4
     3202439.278    13950219.311     3201530.975    13950516.575
     3200969.736    13950667.991     3198953.769    13951206.731
#Sta/Elev= 30
       0   68.12   585.8   61.34  649.86   59.03  705.79   58.61  911.44   50.62
  955.71    48.4  956.22    45.4 1011.02    45.8 1017.02   42.87 1043.82    34.9
 1093.82    35.6 1193.82    23.8 1243.82      38 1293.82    40.6 1343.82    39.2
 1393.82      34 1443.82    32.8 1500.22    44.4 1618.78   47.72 1802.56   46.55
 1877.73   48.06 2010.85   53.27 2150.34   55.31 2513.21   57.48 2789.22   60.81
 2882.24   60.44 3206.81   63.04 3308.07   65.73 3370.84    64.2 3623.73   66.45
#Mann= 3 ,-1 , 0
       0     .11       0 1011.02     .05       0 1500.22     .12       0
Bank Sta=1011.02,1500.22
XS Rating Curve= 0
Exp/Cntr=.3,.1

Type RM Length L Ch R = 1 ,6364.291,1529.65,1248.07,1061.67
BEGIN DESCRIPTION:
481v34
Bank Station offset =      3021
END DESCRIPTION:
XS GIS Cut Line= 6
     3201865.393    13948868.992     3200703.283    13949613.638
     3199983.257    13950032.157     3199722.269     13950176.61
     3199582.588    13950243.927     3198877.813    13950936.667
#Sta/Elev= 30
       0   67.82  218.09   67.76   457.7   64.41   550.8   60.29  709.43   48.62
   763.7   46.48  812.81    42.3 1349.48   41.76 1470.27   45.86 1487.65   47.78
 1521.23   46.25 1583.72   48.08 1769.08    43.7 1779.18      40 1819.18    35.7
 1859.18    38.1 1899.18    36.6 1979.18    24.8 2019.18    25.6 2059.18    33.7
 2139.18   42.73 2141.18    44.3 2235.45   42.53 2283.97   43.93 2332.08    48.2
 2394.99      50 2625.91   49.95 2829.17   55.78 3224.95   58.21 3655.13   66.49
#Mann= 3 ,-1 , 0
       0     .11       0 1769.08     .06       0 2141.18     .12       0
Bank Sta=1769.08,2141.18
XS Rating Curve= 0
Exp/Cntr=.3,.1

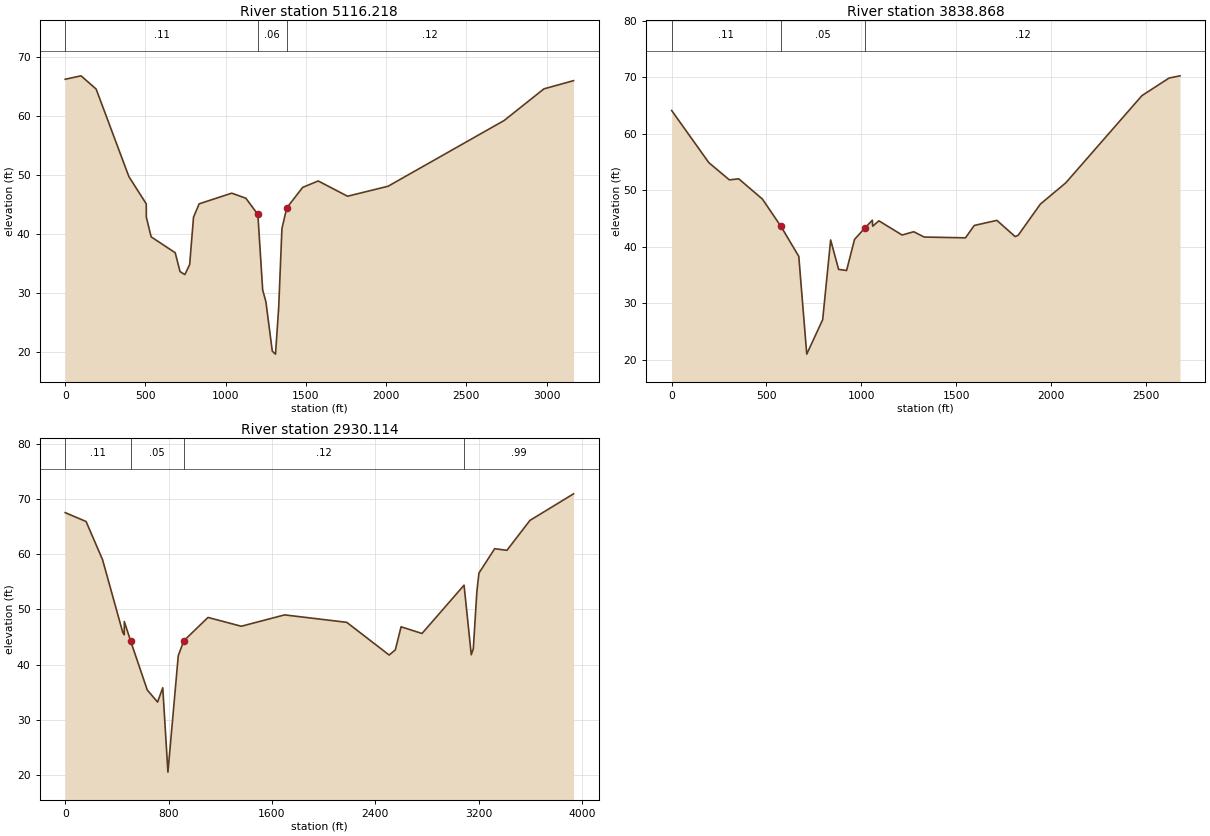
Type RM Length L Ch R = 1 ,5116.218,1237.32,1277.35,1207.1
BEGIN DESCRIPTION:
481v35 and 481v36 (on left side),added v36 manually.
Bank Station offset =      3689
END DESCRIPTION:
XS GIS Cut Line= 6
     3199561.412    13948117.877     3199291.348    13948472.336
     3199296.797    13948871.881     3199351.377    13949168.901
     3199035.173    13950289.082     3198489.596    13950945.107
#Sta/Elev= 30
       0   66.24   98.64   66.82  192.72   64.58  396.92   49.72   505.1    45.1
   505.6   42.83   535.6    39.5   685.6    36.8   715.6    33.6   745.6    33.1
   775.6    34.8   799.6   42.83   834.6    45.1 1037.69   46.91 1125.93   46.05
  1200.6    43.3  1230.6    30.5  1250.6    28.5  1290.6    20.1  1310.6    19.6
  1330.6    27.6  1350.6    40.9  1380.6    44.4 1479.66   47.89 1576.72   48.98
 1759.71   46.39 2012.43   48.09 2735.95   59.25 2983.32   64.61 3167.82      66
#Mann= 3 ,-1 , 0
       0     .11       0  1200.6     .06       0  1380.6     .12       0
Bank Sta=1200.6,1380.6
XS Rating Curve= 0
Exp/Cntr=.3,.1

Type RM Length L Ch R = 1 ,3838.868,853.91,908.75,976.98
BEGIN DESCRIPTION:
481v37
Bank Station offset =      4288
END DESCRIPTION:
XS GIS Cut Line= 6
     3198215.224    13948098.481     3198170.279    13948622.085
     3198158.294    13948753.922     3198122.338    13949155.427
     3198092.698    13949660.969     3197974.788    13950767.878
#Sta/Elev= 30
       0   64.11  196.16   54.88  304.28   51.84  353.75   52.02  478.57   48.44
  576.33    43.6  670.33    38.3  712.33      21  796.33    27.1  838.33    41.2
  880.33      36  922.33    35.8  964.33    41.3 1018.33    43.3 1058.33    44.7
 1059.99   43.64 1092.86   44.59 1215.12   42.08 1276.56   42.66 1331.55   41.72
 1549.57   41.58 1595.55   43.77 1714.99   44.67  1811.1   41.81 1826.92   42.02
 1944.46   47.56 2078.26   51.31 2480.02   66.75 2623.21   69.86  2680.6   70.25
#Mann= 3 ,-1 , 0
       0     .11       0  576.33     .05       0 1018.33     .12       0
Bank Sta=576.33,1018.33
XS Rating Curve= 0
Exp/Cntr=.3,.1

Type RM Length L Ch R = 1 ,2930.114,0,0,0
BEGIN DESCRIPTION:
481v38
Manning's .99 far right of cross section - does not contribute to flow in Luce Bayou.
Bank Station offset =      4205
END DESCRIPTION:
XS GIS Cut Line= 6
      3197505.74    13948128.645      3197480.34    13948187.848
     3197338.523    13948553.825     3197250.507    13948795.402
     3196978.379     13949532.89     3196177.176    13951831.253
#Sta/Elev= 30
       0   67.55   161.7   65.94  289.23   59.01  445.48   45.83  456.92   45.41
   457.5    47.8   507.5    44.2     635    35.4     715    33.2     755    35.8
     795    20.5     875    41.6   917.5    44.3 1105.14   48.55 1362.82   46.95
 1698.36   49.01 2178.88   47.66 2507.34   41.73 2554.94   42.67 2599.39   46.85
 2761.45   45.64 3086.83    54.4  3142.7   41.78 3158.58   42.88 3185.91   53.22
 3202.26    56.6 3323.86   61.01  3418.7   60.72 3596.71   66.14 3934.13   70.96
#Mann= 4 ,-1 , 0
       0     .11       0   507.5     .05       0   917.5     .12       0
 3086.83     .99       0
Bank Sta=507.5,917.5
XS Rating Curve= 0
Exp/Cntr=.3,.1

Chan Stop Cuts=-1